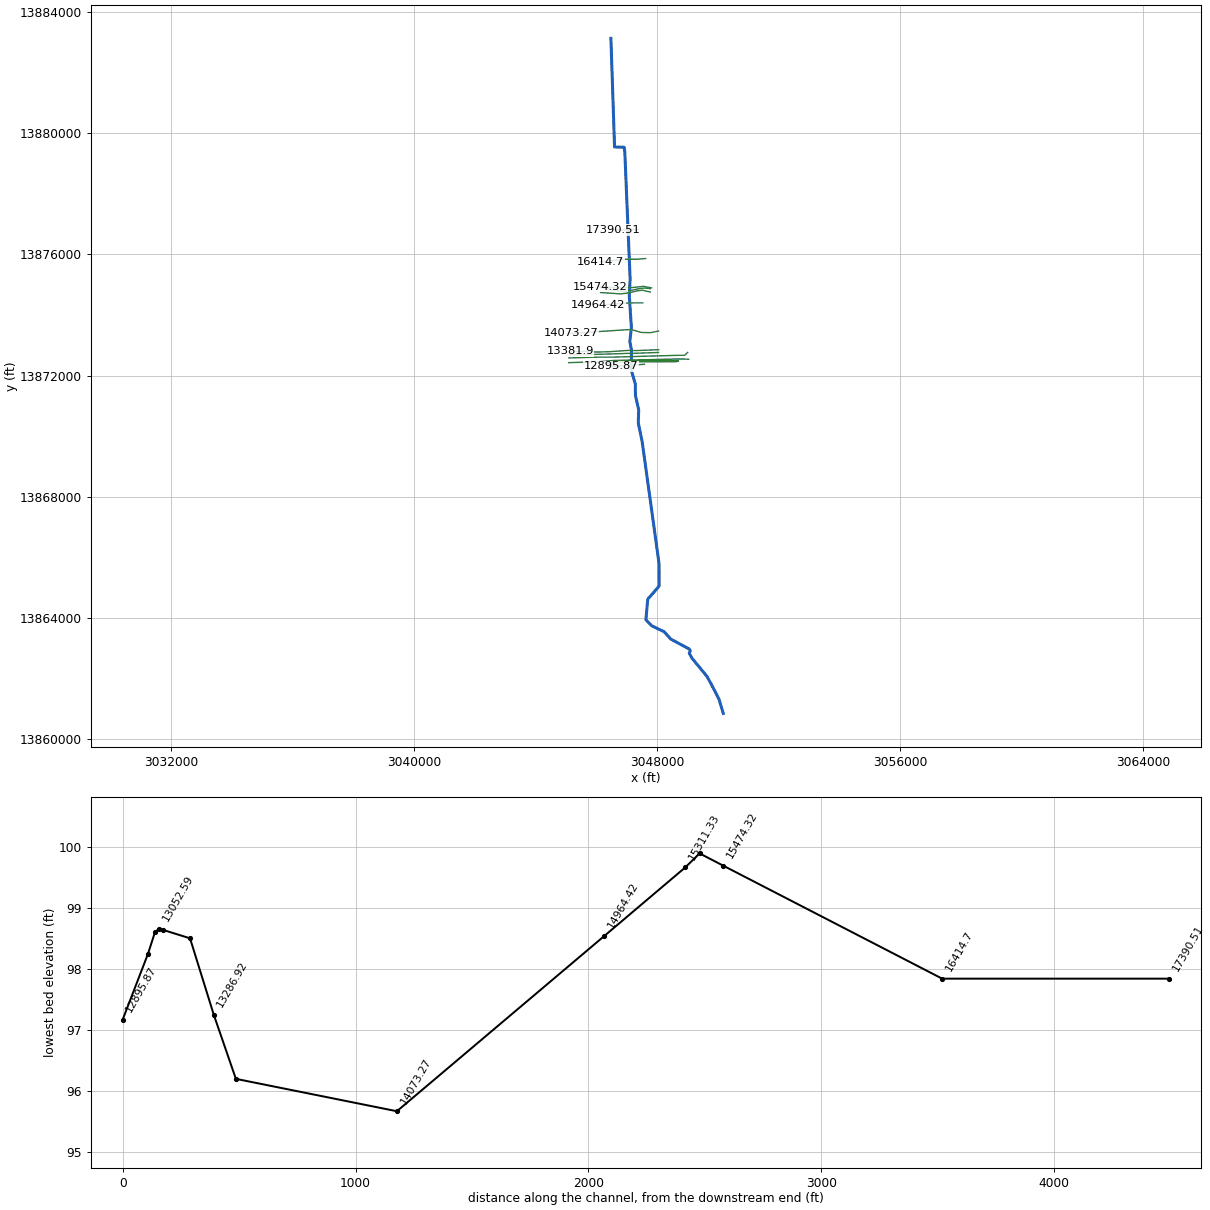
--- W167-01-00.prj (project) ---

Proj Title=W167-01-00 2019 (Re-Study)
Current Plan=p02
Default Exp/Contr=0.3,0.1
English Units
Geom File=g01
Flow File=f01
Flow File=f02
Flow File=f03
Plan File=p01
Plan File=p02
Plan File=p03
Y Axis Title=Elevation
X Axis Title(PF)=Main Channel Distance
X Axis Title(XS)=Station
BEGIN DESCRIPTION:
Tributary 3.9 to Turkey Creek (W167-01-00)
(Flood Hazard & Floodway) Model
10-, 2-, 1-, and 0.2% Events
Filename W167_01_00.prj
Prepared by:  LAN                               Date: 10/29/2012
Reviewed by: HCFCD                          Date: 10/16/2012
STATUS: Final
ADDICKS WATERSHED MODEL UPDATE
HARRIS COUNTY, TEXAS
END DESCRIPTION:
DSS Export Rating Curves= 0
DSS Export Rating Curve Sorted= 0
DSS Export Volume Flow Curves= 0
DXF OffsetX= 0
DXF OffsetY= 0
DXF ScaleX= 1
DXF ScaleY= 10

--- W167-01-00.p02 (plan) ---

Plan Title=Effective Floodway 2019 (Re-Study)
Program Version=4.10
Short Identifier=Eff+ ReStudy FW
Geom File=g01
Flow File=f02
Subcritical Flow
K Sum by GR= 0
Std Step Tol= 0.01
Critical Tol= 0.01
Num of Std Step Trials= 20
Max Error Tol= 0.3
Flow Tol Ratio= 0.001
Split Flow NTrial= 30
Split Flow Tol= 0.02
Split Flow Ratio= 0.02
Log Output Level= 0
Friction Slope Method= 1
Unsteady Friction Slope Method= 2
Unsteady Bridges Friction Slope Method= 1
Parabolic Critical Depth
Global Vel Dist= 0 , 0 , 0
Global Log Level= 0
CheckData=True
Encroach Param=-1 ,0,0, 2
Encroach River=W167-01-00
Encroach Reach=W167-01-00_0082
Encroach Node=17390.51
       1  239.75  399.59
Encroach Node=16414.7
       1  465.91  620.22
Encroach Node=15474.32
       1  610.87  816.35
Encroach Node=15373.11
       1  616.79  767.08
Encroach Node=15311.33
       1  621.64  781.37
Encroach Node=14964.42
       1  291.31  517.86
Encroach Node=14073.27
       1  797.79 1005.41
Encroach Node=13381.9
       1  794.82   989.1
Encroach Node=13286.92
       1  830.68  993.79
Encroach Node=13185.06
       1 1845.18 1969.42
Encroach Node=13067.48
       1 1825.25    1980
Encroach Node=13052.59
       1  1471.6 1619.69
Encroach Node=13034.31
       1 1480.37 1618.54
Encroach Node=13004.85
       1 1473.91    1622
Encroach Node=12895.87
       1  368.92  517.55
Encroach Node=12784.52
       1   448.2  631.47
Encroach Node=11950.98
       1  473.61  642.04
Encroach Node=11872
       1  318.54  434.74
Encroach Node=11797.71
       1   323.5  448.84
Encroach Node=11476.9
       1    84.7  242.31
Encroach Node=11096.04
       1  424.36  591.96
Encroach Node=10907.41
       1  474.91  653.54
Encroach Node=10663.71
       1  699.67    1010
Encroach Node=10617.27
       1 1196.09    1534
Encroach Node=10472.27
       1    1165    1701
Encroach Node=10350.29
       1    1247    1848
Encroach Node=10324.79
       1    1248    1848
Encroach Node=10255.28
       1    1631    2262
Encroach Node=9275.005
       1    3744    4601
Encroach Node=8242.248
       1    4323    5207
Computation Interval=1HOUR
Output Interval=1HOUR
Run HTab= 0
Run UNet= 0
Run PostProcess= 0
Run WQNet= 0
UNET Theta= 1
UNET Theta Warmup= 1
UNET ZTol= 0.02
UNET ZSATol= 0.05
UNET MxIter= 20
UNET MaxInSteps= 0
UNET DtIC= 0
UNET DtMin= 0
UNET MaxCRTS= 20
UNET WFStab= 2
UNET SFStab= 1
UNET WFX= 1
UNET SFX= 1
UNET DSS MLevel= 4
UNET DZMax Abort= 100
UNET Convert EG Bridges= 0
UNET Use Existing IB Tables=-1
UNET Froude Reduction=False
UNET Froude Limit= 1
UNET Froude Power= 10
UNET Time Slicing=0,0, 5
UNET Junction Losses=0
Instantaneous Interval=1HOUR
Write IC File= 0
Write IC File at Sim End=0
Echo Input=False
Echo Parameters=False
Echo Output=False
Write Detailed= 0
WQ AD Non Conservative
WQ ULTIMATE=-1
WQ Max Comp Step=1HOUR
WQ Output Interval=15MIN
WQ Output Selected Increments= 0
WQ Output face flow=0
WQ Output face velocity=0
WQ Output face area=0
WQ Output face dispersion=0
WQ Output cell volume=0
WQ Output cell surface area=0
WQ Output cell continuity=0
WQ Output cumulative cell continuity=0
WQ Output face conc=0
WQ Output face dconc_dx=0
WQ Output face courant=0
WQ Output face peclet=0
WQ Output face adv mass=0
WQ Output face disp mass=0
WQ Output cell mass=0
WQ Output cell source sink temp=0
WQ Output cell source sink nsm=0
WQ Output MaxMinRange=-1
WQ Daily Max Min Mean=-1
WQ Daily Range=0
WQ Daily Time=0
WQ Create Restart=0
WQ Fixed Restart=0
WQ System Summary=0
WQ Use Fixed Temperature=0
Sorting and Armoring Iterations= 10
XS Update Threshold= 0.02
Hydraulics Update Threshold= 0.02
Energy Slope Method= 1
Volume Change Method= 0
XS Weighting Method= 0
Number of US Weighted Cross Sections= 1
Number of DS Weighted Cross Sections= 1
Upstream XS Weight=0.25
Main XS Weight=0.5
Downstream XS Weight=0.25
Number of DS XS's Weighted with US Boundary= 1
Upstream Boundary Weight= 1
Weight of XSs Associated with US Boundary= 0
Number of US XS's Weighted with DS Boundary= 1
Downstream Boundary Weight= 0.5
Weight of XSs Associated with DS Boundary= 0.5
Sediment Output Level= 4
Mass or Volume Output= 0
Output Increment Type= 1
Profile and TS Output Increment= 10
XS Output Flag= 0
XS Output Increment= 10
Disregard all LS=0
Disregard all Conn=0
Disregard all Breaches=0
Disregard all Pumps=0

--- W167-01-00.p01 (plan) ---

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Plan Title=Effective Multi-Profile 2019 (Re-Study)
Short Identifier=Eff+ReStudy MP
Geom File=g01
Flow File=f01
Encroach Param=-1 ,0,0, 0

--- W167-01-00.p03 (plan) ---

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Plan Title=Storage Routing (SV-SQ)
Short Identifier=SV-SQ
Geom File=g01
Flow File=f03
Encroach Param=-1 ,0,0, 0

--- W167-01-00.f02 (steady flow) ---

Flow Title=Effective Floodway 2019
Program Version=4.10
Number of Profiles= 2
Profile Names=100YR,FW
River Rch & RM=W167-01-00,W167-01-00_0082 ,17390.51
    1569    1569
River Rch & RM=W167-01-00,W167-01-00_0082 ,16414.7
    1631    1631
River Rch & RM=W167-01-00,W167-01-00_0082 ,15474.32
    1665    1665
River Rch & RM=W167-01-00,W167-01-00_0082 ,14964.42
    1728    1728
River Rch & RM=W167-01-00,W167-01-00_0082 ,14073.27
    1778    1778
River Rch & RM=W167-01-00,W167-01-00_0082 ,13381.9
    1822    1822
River Rch & RM=W167-01-00,W167-01-00_0082 ,12784.52
    1886    1886
River Rch & RM=W167-01-00,W167-01-00_0082 ,11950.98
    1923    1923
River Rch & RM=W167-01-00,W167-01-00_0082 ,11476.9
    1969    1969
River Rch & RM=W167-01-00,W167-01-00_0082 ,10907.41
    2015    2015
River Rch & RM=W167-01-00,W167-01-00_0082 ,10350.29
    2022    2022
River Rch & RM=W167-01-00,W167-01-00_0082 ,10255.28
    2106    2106
River Rch & RM=W167-01-00,W167-01-00_0082 ,9275.005
    2198    2198
Boundary for River Rch & Prof#=W167-01-00,W167-01-00_0082 , 1
Up Type= 0
Dn Type= 1
Dn Known WS=100.8
Boundary for River Rch & Prof#=W167-01-00,W167-01-00_0082 , 2
Up Type= 0
Dn Type= 1
Dn Known WS=101.8
Observed WS=W167-01-00      ,W167-01-00_0082 ,17390.51,0,107.88,109.35
Observed WS=W167-01-00      ,W167-01-00_0082 ,16414.7 ,0,107.45,108.94
Observed WS=W167-01-00      ,W167-01-00_0082 ,15474.32,0,107.27,108.76
Observed WS=W167-01-00      ,W167-01-00_0082 ,15373.11,0,107.26,108.74
Observed WS=W167-01-00      ,W167-01-00_0082 ,15311.33,0,107.15,108.47
Observed WS=W167-01-00      ,W167-01-00_0082 ,14964.42,0,107.11,108.41
Observed WS=W167-01-00      ,W167-01-00_0082 ,14073.27,0,106.96,108.23
Observed WS=W167-01-00      ,W167-01-00_0082 ,13286.92,0,106.85,108.1
Observed WS=W167-01-00      ,W167-01-00_0082 ,13185.06,0,106.68,107.87
Observed WS=W167-01-00      ,W167-01-00_0082 ,13067.48,0,106.52,107.62
Observed WS=W167-01-00      ,W167-01-00_0082 ,12784.52,0,106.43,107.5
Observed WS=W167-01-00      ,W167-01-00_0082 ,11950.98,0,106.14,107.1
Observed WS=W167-01-00      ,W167-01-00_0082 ,11872   ,0,106.05,106.94
Observed WS=W167-01-00      ,W167-01-00_0082 ,11797.71,0,105.92,106.57
Observed WS=W167-01-00      ,W167-01-00_0082 ,11476.9 ,0,105.83,106.4
Observed WS=W167-01-00      ,W167-01-00_0082 ,11096.04,0,105.73,106.23
Observed WS=W167-01-00      ,W167-01-00_0082 ,10663.71,0,105.68,106.17
Observed WS=W167-01-00      ,W167-01-00_0082 ,10350.29,0,105.47,106
Observed WS=W167-01-00      ,W167-01-00_0082 ,10324.79,0,105.46,105.92
Observed WS=W167-01-00      ,W167-01-00_0082 ,10255.28,0,105.13,105.67
Observed WS=W167-01-00      ,W167-01-00_0082 ,9275.005,0,103.53,104
Observed WS=W167-01-00      ,W167-01-00_0082 ,8242.248,0,101.02,101.17
DSS Import GetInterval= 0
DSS Import GetPeak= 0
DSS Import FillOption= 0

--- W167-01-00.f01 (steady flow) ---

Flow Title=Effective Multi-Profile 2019 (Re-Study)
Program Version=4.10
Number of Profiles= 4
Profile Names=10YR,50YR,100YR,500YR
River Rch & RM=W167-01-00,W167-01-00_0082 ,17390.51
     930    1363    1569    2194
River Rch & RM=W167-01-00,W167-01-00_0082 ,16414.7
     960    1414    1631    2285
River Rch & RM=W167-01-00,W167-01-00_0082 ,15474.32
     976    1442    1665    2336
River Rch & RM=W167-01-00,W167-01-00_0082 ,14964.42
    1005    1493    1728    2429
River Rch & RM=W167-01-00,W167-01-00_0082 ,14073.27
    1029    1533    1778    2503
River Rch & RM=W167-01-00,W167-01-00_0082 ,13381.9
    1049    1569    1822    2568
River Rch & RM=W167-01-00,W167-01-00_0082 ,12784.52
    1078    1621    1886    2663
River Rch & RM=W167-01-00,W167-01-00_0082 ,11950.98
    1096    1651    1923    2719
River Rch & RM=W167-01-00,W167-01-00_0082 ,11476.9
    1116    1688    1969    2787
River Rch & RM=W167-01-00,W167-01-00_0082 ,10907.41
    1137    1725    2015    2855
River Rch & RM=W167-01-00,W167-01-00_0082 ,10350.29
    1141    1731    2022    2867
River Rch & RM=W167-01-00,W167-01-00_0082 ,10255.28
    1178    1798    2106    2992
River Rch & RM=W167-01-00,W167-01-00_0082 ,9275.005
    1219    1872    2198    3129
Boundary for River Rch & Prof#=W167-01-00,W167-01-00_0082 , 1
Up Type= 0
Dn Type= 1
Dn Known WS=97.6
Boundary for River Rch & Prof#=W167-01-00,W167-01-00_0082 , 2
Up Type= 0
Dn Type= 1
Dn Known WS=99.9
Boundary for River Rch & Prof#=W167-01-00,W167-01-00_0082 , 3
Up Type= 0
Dn Type= 1
Dn Known WS=100.8
Boundary for River Rch & Prof#=W167-01-00,W167-01-00_0082 , 4
Up Type= 0
Dn Type= 1
Dn Known WS=102.4
Observed WS=W167-01-00      ,W167-01-00_0082 ,17390.51,0,107.88,109.35,110.11,111.32
Observed WS=W167-01-00      ,W167-01-00_0082 ,16414.7 ,0,107.45,108.94,109.76,110.91
Observed WS=W167-01-00      ,W167-01-00_0082 ,15474.32,0,107.27,108.76,109.58,110.69
Observed WS=W167-01-00      ,W167-01-00_0082 ,15373.11,0,107.26,108.74,109.56,110.67
Observed WS=W167-01-00      ,W167-01-00_0082 ,15311.33,0,107.15,108.47,109.17,110.37
Observed WS=W167-01-00      ,W167-01-00_0082 ,14964.42,0,107.11,108.41,109.12,110.31
Observed WS=W167-01-00      ,W167-01-00_0082 ,14073.27,0,106.96,108.23,108.94,110.11
Observed WS=W167-01-00      ,W167-01-00_0082 ,13286.92,0,106.85,108.1,108.81,110.02
Observed WS=W167-01-00      ,W167-01-00_0082 ,13185.06,0,106.68,107.87,108.57,109.75
Observed WS=W167-01-00      ,W167-01-00_0082 ,13067.48,0,106.52,107.62,108.17,109.75
Observed WS=W167-01-00      ,W167-01-00_0082 ,12784.52,0,106.43,107.5,108.04,109.63
Observed WS=W167-01-00      ,W167-01-00_0082 ,11950.98,0,106.14,107.1,107.61,109.22
Observed WS=W167-01-00      ,W167-01-00_0082 ,11872   ,0,106.05,106.94,107.41,108.94
Observed WS=W167-01-00      ,W167-01-00_0082 ,11797.71,0,105.92,106.57,106.87,107.61
Observed WS=W167-01-00      ,W167-01-00_0082 ,11476.9 ,0,105.83,106.4,106.64,107.3
Observed WS=W167-01-00      ,W167-01-00_0082 ,11096.04,0,105.73,106.23,106.42,106.94
Observed WS=W167-01-00      ,W167-01-00_0082 ,10663.71,0,105.68,106.17,106.35,106.9
Observed WS=W167-01-00      ,W167-01-00_0082 ,10350.29,0,105.47,106,106.19,106.77
Observed WS=W167-01-00      ,W167-01-00_0082 ,10324.79,0,105.46,105.92,106.11,106.7
Observed WS=W167-01-00      ,W167-01-00_0082 ,10255.28,0,105.13,105.67,105.89,106.53
Observed WS=W167-01-00      ,W167-01-00_0082 ,9275.005,0,103.53,104,104.22,104.29
Observed WS=W167-01-00      ,W167-01-00_0082 ,8242.248,0,101.02,101.17,101.22,102.4
DSS Import GetInterval= 0
DSS Import GetPeak= 0
DSS Import FillOption= 0

--- W167-01-00.f03 (steady flow) ---

Flow Title=Storage Routing Flows
Program Version=4.10
Number of Profiles= 8
Profile Names=0.2,0.4,0.6,0.8,1,1.2,1.5,2
River Rch & RM=W167-01-00,W167-01-00_0082 ,17390.51
     445     890    1335    1780    2225    2670    3338    4450
Boundary for River Rch & Prof#=W167-01-00,W167-01-00_0082 , 1
Up Type= 0
Dn Type= 3
Dn Slope=0.00056
Boundary for River Rch & Prof#=W167-01-00,W167-01-00_0082 , 2
Up Type= 0
Dn Type= 3
Dn Slope=0.00056
Boundary for River Rch & Prof#=W167-01-00,W167-01-00_0082 , 3
Up Type= 0
Dn Type= 3
Dn Slope=0.00056
Boundary for River Rch & Prof#=W167-01-00,W167-01-00_0082 , 4
Up Type= 0
Dn Type= 3
Dn Slope=0.00056
Boundary for River Rch & Prof#=W167-01-00,W167-01-00_0082 , 5
Up Type= 0
Dn Type= 3
Dn Slope=0.00056
Boundary for River Rch & Prof#=W167-01-00,W167-01-00_0082 , 6
Up Type= 0
Dn Type= 3
Dn Slope=0.00056
Boundary for River Rch & Prof#=W167-01-00,W167-01-00_0082 , 7
Up Type= 0
Dn Type= 3
Dn Slope=0.00056
Boundary for River Rch & Prof#=W167-01-00,W167-01-00_0082 , 8
Up Type= 0
Dn Type= 3
Dn Slope=0.00056
DSS Import GetInterval= 0
DSS Import GetPeak= 0
DSS Import FillOption= 0

--- W167-01-00.g01 (geometry) ---

Geom Title=W167-01-00 2019 (Re-Study)
Program Version=4.10

River Reach=W167-01-00      ,W167-01-00_0082
Reach XY= 30
3046479.4780878613883124.05642813046599.9210884413879540.9251429
3046917.0165828613879532.88644513046937.6608985213879362.3513531
3047112.6205223713875188.32623663047084.4909854413874638.2548302
3047154.0968173613873583.48955133047102.1490866113873120.0662655
3047158.2470715213872836.62588753047147.3133663513872191.9116258
3047284.7520678613871716.9991898 3047287.141170713871339.8044061
 3047393.749225213870874.00021963047381.5005620313870433.0004454
3047509.2486661113869817.00167743048063.44572045 13865807.153726
3048068.17963485 13865055.4977493047692.6147691913864624.1767613
3047631.59848702 13863946.1613853047821.4849182813863748.3848777
3048228.6100882713863551.66053363048456.36849102 13863304.965817
3049055.48376261 13862983.0530753049092.3038989513862924.6670369
3049060.2180051113862841.03268983049151.2161826913862675.8683219
3049636.7152116913862084.64279833049788.72967145 13861813.752264
3050037.52805837 13861325.6233193050179.0225260313860858.0081125

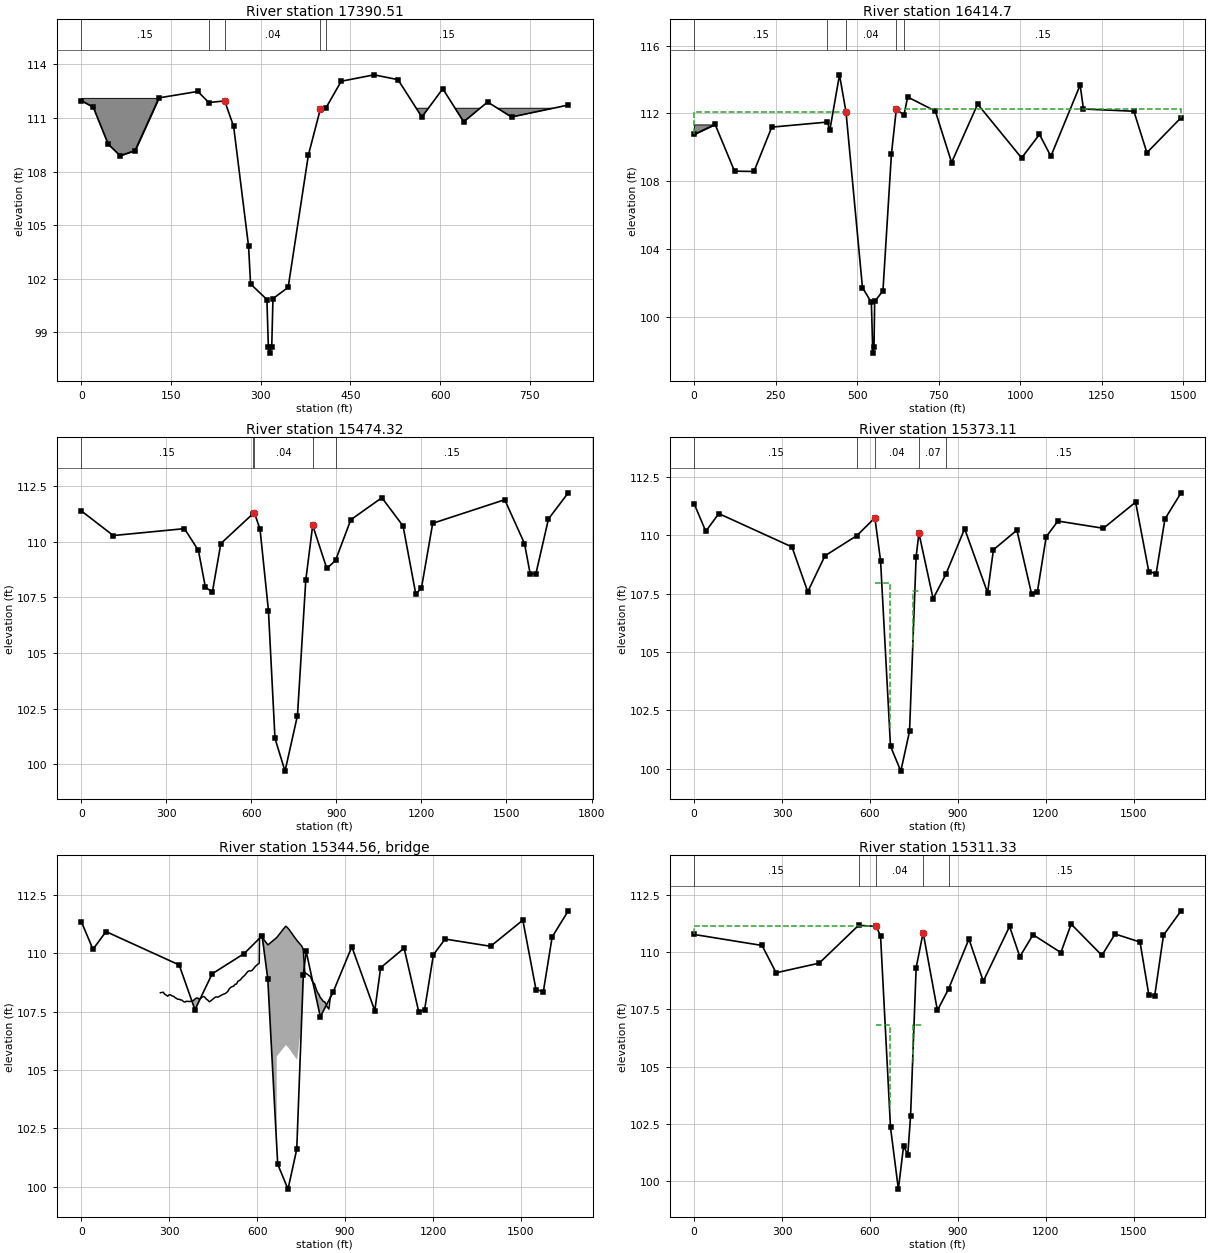
Type RM Length L Ch R = 1 ,17390.51,983.79,975.8,977.43
Node Name=M
XS GIS Cut Line= 2
3047357.9999528713876818.00014263046543.9999404413876801.9998465
#Sta/Elev= 30
       0  111.97   19.98   111.6   44.95  109.53   64.93  108.89   89.91  109.17
  129.87  112.12   194.8  112.48  213.15  111.86  239.75  111.95  254.74  110.52
  279.71  103.81  283.03  101.71  310.32  100.84  312.82   98.18   314.8   97.84
  318.42   98.19  320.48  100.89  345.88  101.52  379.61  108.91  399.59  111.48
  409.08  111.56  434.55  113.05  489.49  113.41  529.45  113.14  569.41  111.05
  604.37  112.63  639.34  110.78   679.3  111.89  719.26  111.05  814.16  111.72
#Mann= 5 ,-1 , 0
       0     .15       0  213.15     .07       0  239.75     .04       0
  399.59     .07       0  409.08     .15       0
#Block Obstruct= 2 ,-1
       0  129.87  112.12  559.42  814.16  111.54
Bank Sta=239.75,399.59
XS Rating Curve= 0 ,0
Exp/Cntr=0.3,0.1

Type RM Length L Ch R = 1 ,16414.7 ,940.61,940.38,944.65
XS GIS Cut Line= 5
    3047623.100813875861.1378831 3047345.999976913875838.0001341
 3047192.999954813875838.0001341 3046969.000074713875838.0001341
 3046135.0001023 13875751.999978
#Sta/Elev= 30
       0  110.76   64.55  111.35  124.14  108.59  183.72  108.57  238.34  111.19
  409.04  111.49  416.26     111     446  114.28  465.91  112.09  516.41  101.71
   543.7  100.84  548.18   97.84   551.8   98.19  553.86  100.89  579.26  101.52
  605.29  109.61  620.22  112.24  643.77  111.91  655.06  112.97  739.91  112.14
  789.81   109.1  869.66  112.55 1004.41  109.37  1059.3  110.76 1094.24  109.47
 1184.07  113.68 1194.05  112.26 1348.76  112.13 1388.69  109.68 1493.49  111.75
#Mann= 5 ,-1 , 0
       0     .15       0  409.04     .07       0  465.91     .04       0
  620.22     .07       0  643.77     .15       0
#XS Ineff= 2 , 0
       0  465.91  112.09  620.22       0  112.24
Permanent Ineff=
       F       F
#Block Obstruct= 1 ,-1
       0   64.55  111.35
Bank Sta=465.91,620.22
XS Rating Curve= 0 ,0
Exp/Cntr=0.3,0.1

Type RM Length L Ch R = 1 ,15474.32,98.35,101.21,111.27
XS GIS Cut Line= 6
  3047819.86484213874891.5919219 3047554.999886913874943.9999536
 3047167.000006813874902.0000376 3047010.999990713874897.0000476
 3046777.000130613874891.0000596 3046111.000150313874935.9999696
#Sta/Elev= 30
       0  111.39  112.91  110.28  363.86  110.59  413.26  109.61  437.96  107.95
  462.66  107.75   492.3  109.92  605.65  111.26  610.87   111.3  630.63  110.56
  660.27  106.91  683.37  101.16   718.8   99.69  762.69  102.19  791.96  108.27
  816.35  110.74  866.15   108.8  896.86  109.16  950.82  110.99 1060.39  111.98
 1135.11  110.71 1179.94  107.66 1199.87  107.91 1239.72  110.83 1493.78  111.89
 1563.52  109.92 1583.44  108.57 1603.37  108.54  1648.2  111.03 1717.94   112.2
#Mann= 5 ,-1 , 0
       0     .15       0  605.65     .07       0  610.87     .04       0
  816.35     .07       0  896.86     .15       0
#XS Ineff= 2 ,-1
       0  610.87   111.3  816.35 1717.94  110.74
Permanent Ineff=
       F       F
Bank Sta=610.87,816.35
XS Rating Curve= 0 ,0
Exp/Cntr=0.5,0.3

Type RM Length L Ch R = 1 ,15373.11,62.41,61.79,63.96
BEGIN DESCRIPTION:
Upstream Section - ACACIA ARBOR LN
END DESCRIPTION:
Node Name=L
XS GIS Cut Line= 6
  3047775.50371113874866.4751743 3047606.883969513874887.7152893
 3047443.566382813874874.5739114 3047001.623697113874779.5284978
 3046787.072945113874782.0012618 3046139.080146613874907.3041608
#Sta/Elev= 30
       0  111.36      40  110.17   84.29  110.93  333.97   109.5  387.81  107.58
  446.44  109.12   555.9  109.99  616.79  110.75  636.18  108.91  670.07  100.96
  705.25   99.89  735.03   101.6  757.55  109.09  767.08  110.09  815.42  107.28
   858.6  108.32  922.95  110.28 1001.23  107.54 1021.23  109.38 1101.23  110.22
 1151.23  107.49 1171.23  107.59 1201.23  109.94 1241.22  110.61 1396.22   110.3
 1506.22  111.42 1551.22  108.44 1576.22  108.36 1606.22   110.7 1661.22  111.82
#Mann= 5 ,-1 , 0
       0     .15       0   555.9     .07       0  616.79     .04       0
  767.08     .07       0   858.6     .15       0
#XS Ineff= 4 ,-1
       0  616.79  110.75  616.79   666.8  107.96  745.81  767.08  107.61
  767.08 1661.22  110.09
Permanent Ineff=
       F       F       F       F
Bank Sta=616.79,767.08
XS Rating Curve= 0 ,0
Exp/Cntr=0.5,0.3

Type RM Length L Ch R = 3 ,15344.56,,,
BEGIN DESCRIPTION:
ACACIA ARBOR LN
END DESCRIPTION:
Node Name=ACACIA ARBOR
Bridge Culvert--1,0,-1,-1, 0
Deck Dist Width WeirC Skew NumUp NumDn MinLoCord MaxHiCord MaxSubmerge Is_Ogee
7.5,50.3,2.6,0, 120, 121, , , 0.98, 0, 0,0,,
     270  274.92  279.84  284.76  289.68  294.61  299.53  304.45  309.37  314.29
  319.21  324.13  329.05  333.97  338.87  343.76  348.66  353.55  358.44  363.34
  368.23  373.12  378.02  382.91  387.81   392.7  397.59  402.49  407.38  412.27
  417.15  422.04  426.92   431.8  436.68  441.56  446.44  451.32   456.2  461.08
  465.96  470.85  475.73  480.61  485.49  490.37  495.25  500.13  505.01  509.89
  514.77  519.66  524.54  529.42   534.3  539.18  544.06  548.94  553.79  558.63
  563.48  568.33  573.17  578.02  582.87  587.71  592.56   597.4  602.25   607.1
   608.2   636.9  646.09   646.2  646.31   666.4  666.51   666.6   666.7   666.8
   669.6   695.9   697.4   700.6   701.9   702.6   704.5     706   711.2   723.9
   734.5   736.4   751.2   751.3  751.39   751.5   751.6  756.79   756.9  757.01
  762.31  767.08  771.84   776.6  781.37  786.13  791.01  795.89  800.78  805.66
  810.54  815.43  820.31  825.19  830.07  834.96  839.84  844.72   849.6  854.49
  108.31  108.32  108.33  108.24  108.21  108.16  108.22  108.22  108.17  108.16
  108.11  108.07  108.03  108.03     108  107.99  107.93  107.91  107.94  107.94
  107.93  107.94  107.95  107.98  108.04  108.08  108.08  108.03  108.07  108.12
  108.15  108.11  108.03  107.99  107.92  107.96  108.01  108.06  108.11  108.13
  108.12  108.15  108.19  108.22  108.25  108.27  108.31  108.37  108.48  108.54
  108.57  108.59  108.67  108.68   108.8  108.83  108.88  108.96  109.01  109.07
  109.15  109.22  109.25  109.24  109.27  109.34  109.42  109.48  109.53  109.57
  110.82  110.36  110.46  110.46  110.46  110.67  110.67  110.67  110.67  110.68
  110.72  111.14  111.16  111.13  111.12  111.11  111.08  111.06  110.98  110.75
  110.57  110.54  110.32  110.32  110.32  110.32  110.32  110.18  110.18  110.18
  109.21  109.12   109.1  109.04  109.01  108.86  108.73  108.69  108.48  108.33
  108.24   108.1  108.03  107.94  107.92  107.83  107.68  107.61  108.12  108.25
                                                                                
                                                                                
                                                                                
                                                                                
                                                                                
                                                                                
                                                                                
                                                                  105.57  105.58
  105.62  106.04  106.06  106.03  106.02  106.01  105.98  105.96  105.88  105.65
  105.47  105.44  105.22  105.22  105.22
                                                                                
                                                                                
     270  274.92  279.84  284.76  289.68  294.61  299.53  304.45  309.37  314.29
  319.21  324.13  329.05  333.97  338.87  343.76  348.66  353.55  358.44  363.34
  368.23  373.12  378.02  382.91  387.81   392.7  397.59  402.49  407.38  412.27
  417.15  422.04  426.92   431.8  436.68  441.56  446.44  451.32   456.2  461.08
  465.96  470.85  475.73  480.61  485.49  490.37  495.25  500.13  505.01  509.89
  514.77  519.66  524.54  529.42   534.3  539.18  544.06  548.94  553.79  558.63
  563.48  568.33  573.17  578.02  582.87  587.71  592.56   597.4  602.25   607.1
   608.2   636.9  646.09   646.2  646.31   666.4  666.51   666.6   666.7   666.8
   669.6   695.9   697.4   700.6   701.9   702.6   704.5     706   711.2   723.9
   734.5   736.4   751.2   751.3  751.39   751.5   751.6  756.79   756.9  757.01
  762.31  767.08  771.84   776.6  781.37  786.13  791.01  795.89  800.78  805.66
  810.54  815.43  820.31  825.19  830.07  834.96  839.84  844.72   849.6  854.49
  859.37
  108.31  108.32  108.33  108.24  108.21  108.16  108.22  108.22  108.17  108.16
  108.11  108.07  108.03  108.03     108  107.99  107.93  107.91  107.94  107.94
  107.93  107.94  107.95  107.98  108.04  108.08  108.08  108.03  108.07  108.12
  108.15  108.11  108.03  107.99  107.92  107.96  108.01  108.06  108.11  108.13
  108.12  108.15  108.19  108.22  108.25  108.27  108.31  108.37  108.48  108.54
  108.57  108.59  108.67  108.68   108.8  108.83  108.88  108.96  109.01  109.07
  109.15  109.22  109.25  109.24  109.27  109.34  109.42  109.48  109.53  109.57
  110.82  110.36  110.46  110.46  110.46  110.67  110.67  110.67  110.67  110.68
  110.72  111.14  111.16  111.13  111.12  111.11  111.08  111.06  110.98  110.75
  110.57  110.54  110.32  110.32  110.32  110.32  110.32  110.18  110.18  110.18
  109.21  109.12   109.1  109.04  109.01  108.86  108.73  108.69  108.48  108.33
  108.24   108.1  108.03  107.94  107.92  107.83  107.68  107.61  108.12  108.25
  108.23
                                                                                
                                                                                
                                                                                
                                                                                
                                                                                
                                                                                
                                                                                
                                                                  105.53  105.54
  105.58     106  106.02  105.99  105.98  105.97  105.94  105.92  105.84  105.61
  105.43   105.4  105.18  105.18  105.18
                                                                                
                                                                                
        
BR Coef=-1 , 0 , 0 ,, 0 ,,,0.8,-1,,0,
WSPro=,,,, 1 ,,,, 0 ,,,, 0 ,,,,-1 ,-1 ,-1 , 0 , 0 , 0 , 0 , 0
BC Design=,, 0 ,, 0 ,,,,,,
BC Use User HTab Curves=0
BC User HTab FreeFlow(D)= 0

Type RM Length L Ch R = 1 ,15311.33,360.13,346.91,340.85
BEGIN DESCRIPTION:
Downstream Section - ACACIA ARBOR LN
END DESCRIPTION:
Node Name=K
XS GIS Cut Line= 6
  3047779.79536913874755.1942289 3047516.961249113874815.8794749
 3047375.940533813874800.1245852 3047011.075121813874718.8632648
 3046797.864590213874694.7917906 3046139.351471513874739.0203767
#Sta/Elev= 30
       0  110.76   231.9  110.28  279.84  109.09  426.92  109.51  561.35  111.16
  621.64  111.11  636.18  110.68   670.1  102.35  696.92   99.66  714.68  101.54
  728.97  101.16   738.5  102.84  757.55  109.31  781.37  110.84  830.07  107.45
  868.35  108.39  937.63  110.56  986.55  108.72 1076.23  111.11 1111.23  109.79
 1156.23  110.75 1251.22  109.97 1286.22  111.21 1391.22  109.85 1436.23  110.78
 1521.22  110.43 1551.23  108.13 1571.23  108.08 1601.23  110.73 1661.22  111.79
#Mann= 5 ,-1 , 0
       0     .15       0  561.35     .07       0  621.64     .04       0
  781.37     .07       0  868.35     .15       0
#XS Ineff= 4 ,-1
       0  621.64  111.11  621.64   666.8   106.8  745.27  781.37   106.8
  781.37 1661.23  110.84
Permanent Ineff=
       F       F       F       F
Bank Sta=621.64,781.37
XS Rating Curve= 0 ,0
Exp/Cntr=0.5,0.3

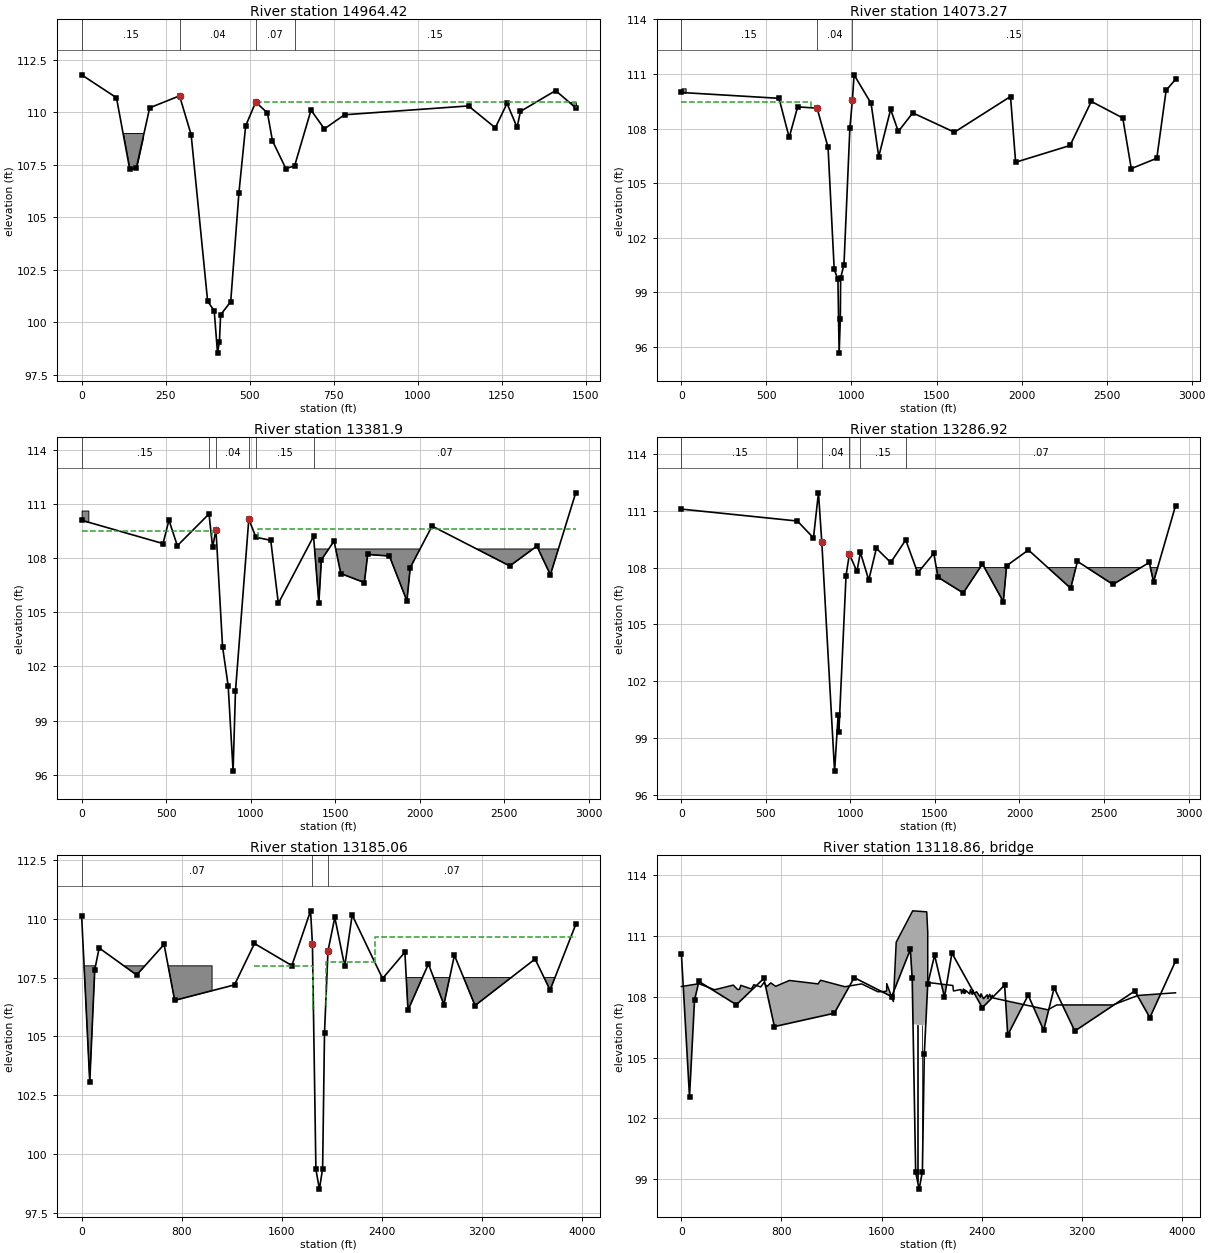
Type RM Length L Ch R = 1 ,14964.42,907.88,891.15,897.71
XS GIS Cut Line= 4
3047528.9999389513874398.00006133047212.9999147813874397.0000634
 3047060.999890713874395.00006743046061.9999201913874318.9998913
#Sta/Elev= 30
       0  111.78  103.69  110.69  143.19  107.28  162.94  107.36  202.44  110.21
  291.31  110.78  325.81  108.93  374.85  101.01  394.46  100.55  404.27   98.54
  409.98   99.09  413.47  100.36   443.5  100.99  468.01  106.18  487.95  109.35
  517.86  110.48  552.75  109.97   567.7  108.64  607.58  107.32  633.67  107.45
  682.35   110.1  722.22  109.21  782.04  109.88 1150.89   110.3 1230.65  109.26
 1265.54  110.42 1295.44  109.28 1305.41  110.04 1410.09  111.03  1469.9  110.21
#Mann= 4 ,-1 , 0
       0     .15       0  291.31     .04       0  517.86     .07       0
  633.67     .15       0
#XS Ineff= 2 ,-1
       0  291.31  110.78  517.86  1469.9  110.48
Permanent Ineff=
       F       F
#Block Obstruct= 2 ,-1
   118.5  182.69  109.01 1410.09  1469.9  110.48
Bank Sta=291.31,517.86
XS Rating Curve= 0 ,0
Exp/Cntr=0.3,0.1

Type RM Length L Ch R = 1 ,14073.27,699.71,691.38,719.02
XS GIS Cut Line= 6
  3048048.99988313873467.9999529 3047785.000083113873416.0000568
 3047480.000036913873422.0000449 3047217.999904813873499.9998889
 3047060.999890713873516.9998548 3045165.833405513873391.3993843
#Sta/Elev= 30
       0  109.98  574.13  109.66  633.77  107.51  683.48  109.19  797.79  109.12
   862.3  106.97  898.54  100.27  920.38   99.72  927.45   95.67  934.56   97.55
   936.3    99.8  955.93  100.53  990.61  108.01 1005.41  109.58 1015.41  110.95
 1115.38  109.38 1160.37  106.46 1230.35  109.05 1275.34  107.84 1360.31  108.86
 1605.24   107.8 1935.14  109.76 1965.14  106.15 2285.14  107.07 2410.14  109.49
 2595.14  108.58 2645.14   105.8 2795.14  106.37 2850.14   110.1 2905.15   110.7
#Mann= 3 , 0 , 0
       0     .15       0  797.79     .04       0 1005.41     .15       0
#XS Ineff= 2 , 0
       0     763  109.46 1015.41       0  109.46
Permanent Ineff=
       F       F
#Block Obstruct= 2 , 0
       0   24.91  110.21 1935.14       0   108.5
Bank Sta=797.79,1005.41
XS Rating Curve= 0 ,0
Exp/Cntr=0.3,0.1

Type RM Length L Ch R = 1 ,13381.9 ,101.44,94.98,100.94
XS GIS Cut Line= 6
  3048052.88373313872854.9499979 3047323.469510113872824.3536023
 3047034.592135113872830.2712414 3046431.765584913872787.6564973
 3046031.923208713872776.4252205 3045132.537868413872809.6807314
#Sta/Elev= 30
       0  110.09  481.74   108.8   516.5   110.1  566.17  108.68  753.63  110.44
  774.89   108.6  794.82  109.56  833.78  103.09  867.12  100.91  896.13    96.2
   910.1  100.61   989.1  110.15 1031.16  109.15 1118.88  108.98 1163.83  105.49
 1372.22   109.2 1403.57  105.52 1418.55   107.9 1493.47  108.94 1533.43  107.14
 1672.71  106.64 1692.46   108.2 1820.86  108.11 1924.56  105.63 1944.31  107.47
 2073.32  109.77 2533.32  107.56 2693.31  108.66 2773.31  107.07 2923.32  111.61
#Mann= 6 ,-1 , 0
       0     .15       0  753.63     .07       0  794.82     .04       0
   989.1     .07       0 1031.16     .15       0 1372.22     .07       0
#XS Ineff= 2 , 0
       0  769.91  109.47 1043.97       0  109.59
Permanent Ineff=
       F       F
#Block Obstruct= 2 ,-1
       0   39.73  110.63  1378.6 2923.32   108.5
Bank Sta=794.82,989.1
XS Rating Curve= 0 ,0
Exp/Cntr=0.3,0.1

Type RM Length L Ch R = 1 ,13286.92,103.85,101.86,113.51
XS GIS Cut Line= 6
  3048047.99988513872763.0000505 3047287.000094913872736.0001045
 3047029.999952713872732.0001125 3046425.999848413872712.0001525
 3046026.157472213872700.7688758 3045126.289193213872685.3820955
#Sta/Elev= 30
       0  111.09  686.25  110.46  781.25  109.57  810.91  111.95  830.68  109.33
  906.17   97.25  927.34  100.22  931.55   99.32  974.02  107.58  993.79  108.71
 1038.49   107.8 1058.99   108.8 1108.41  107.34 1153.36  109.02 1238.27  108.27
 1326.96  109.46 1398.09  107.72 1492.98  108.75 1517.95  107.49 1667.28  106.66
 1780.86  108.19 1904.32   106.2 1924.07   108.1 2052.83  108.93 2302.83  106.91
 2342.83  108.33 2552.83  107.11 2767.83  108.27 2792.83  107.25 2922.84  111.26
#Mann= 6 ,-1 , 0
       0     .15       0  686.25     .07       0  830.68     .04       0
  993.79     .07       0 1058.99     .15       0 1326.96     .07       0
#XS Ineff= 3 ,-1
       0  810.91  109.84  993.79 1326.96  108.71 1326.96 2922.84  109.22
Permanent Ineff=
       F       F       F
#Block Obstruct= 1 ,-1
 1326.96 2922.84     108
Bank Sta=830.68,993.79
XS Rating Curve= 0 ,0
Exp/Cntr=0.5,0.3

Type RM Length L Ch R = 1 ,13185.06,117.61,117.58,117.59
BEGIN DESCRIPTION:
Upstream Section - TANNER ROAD
END DESCRIPTION:
Node Name=J
XS GIS Cut Line= 6
  3049007.09409513872761.4583869 3048903.192072413872667.6268817
 3048643.192920513872666.9106758 3046544.031108413872609.2100038
 3046044.032436513872608.0439956 3045094.407039113872581.3695083
#Sta/Elev= 30
       0  110.14      65  103.06     105  107.83     140  108.76  439.87  107.61
  659.14  108.91  743.85  106.53 1222.26  107.19 1381.73  108.95 1680.73  108.01
 1830.23  110.34 1845.18  108.91 1872.85   99.34 1900.82    98.5 1926.59   99.37
 1941.69  105.16 1969.42  108.63 2023.96  110.06  2103.3  107.98 2162.81  110.16
 2405.78  107.46 2584.15  108.58  2608.9  106.11 2772.27  108.08 2896.03  106.35
 2980.19  108.45 3144.99  106.31 3624.99  108.29 3744.99  106.97    3950  109.76
#Mann= 3 ,-1 , 0
       0     .07       0 1845.18     .04       0 1969.42     .07       0
#XS Ineff= 4 ,-1
       0 1381.73  108.95 1381.73 1853.52  108.01 1950.59 2346.28  108.18
 2346.28    3950  109.22
Permanent Ineff=
       F       F       F       F
#Block Obstruct= 2 ,-1
       0 1042.86     108 2346.28    3950   107.5
Bank Sta=1845.18,1969.42
XS Rating Curve= 0 ,0
Exp/Cntr=0.5,0.3

Type RM Length L Ch R = 3 ,13118.86,,,
BEGIN DESCRIPTION:
TANNER ROAD
W671_300
END DESCRIPTION:
Node Name=TANNER ROAD
Bridge Culvert--1,0,-1,-1, 0
Deck Dist Width WeirC Skew NumUp NumDn MinLoCord MaxHiCord MaxSubmerge Is_Ogee
22,92.3,2.6,0, 60, 60, , , 0.98, 0, 0,0,,
       0     140     265  414.95  449.83  464.78  474.75  559.47   579.4  634.22
  659.14  684.05  713.95  753.82  863.46 1092.69 1112.63 1306.98 1441.53  1571.1
 1635.88 1640.87 1642.01 1694.44 1717.25 1848.95 1851.68 1959.53 1961.43  1969.4
 1969.51 2170.09    2175    2235    2240    2255    2260    2265    2270    2275
    2305    2310    2325    2330    2335    2360    2390    2395    2415    2445
    2450    2465    2475    2485    2495    2930    3000    3450    3650    3950
  108.51  108.65  108.35  108.58  108.36  108.37  108.57  108.39   108.6  108.49
   108.7  108.51  108.69  108.52  108.81  108.64  108.82   108.5  108.64  108.25
  108.27  108.31  108.65  107.77   110.7  112.25  112.25   112.2   112.2  111.21
  108.71  108.56  108.29  108.36  108.16  108.39  108.17  108.35  108.19  108.31
  108.14  108.35  108.12  108.33  108.16  108.25  107.98  108.15  107.91   108.1
  107.92  108.13  107.94  108.08  107.94  107.36   107.6   107.6  108.07   108.2
                                                                                
                                                                                
                                                  106.64  106.58
                                                                                
                                                                                
                                                                                
       0     140     265  414.95  449.83  474.75  559.47   579.4  634.22  659.14
  684.05  753.82  863.46 1092.69 1112.63 1306.98 1441.53  1541.2 1635.88 1637.51
 1737.31 1824.24 1835.41 1835.75 1843.69 1845.53  1953.6 1955.61 1963.54  1975.2
 1997.45 2001.79  2164.3    2165    2170    2185    2235    2240    2255    2260
    2265    2305    2310    2325    2330    2335    2360    2390    2395    2415
    2445    2450    2465    2475    2485    2930    3000    3450    3650    3950
  108.51  108.65  108.35  108.58  108.36  108.57  108.39   108.6  108.49   108.7
  108.51  108.52  108.81  108.64  108.82   108.5  108.64  108.29  108.27  108.65
  108.99  109.01  108.73  111.25  112.23  112.23  112.22  112.22   111.2  110.78
  108.75  108.68  108.56  108.25  108.43  108.25  108.36  108.16  108.39  108.17
  108.35  108.14  108.35  108.12  108.33  108.16  108.25  107.98  108.15  107.91
   108.1  107.92  108.13  107.94  108.08  107.36   107.6   107.6  108.07   108.2
                                                                                
                                                                                
                                          106.66  106.64
                                                                                
                                                                                
                                                                                
Pier Skew, UpSta & Num, DnSta & Num=  ,1886.66, 4 ,1880.88, 4 , 3 , 3 , 0 ,,
     1.5     1.5     2.5     2.5
      98   104.1  104.11  106.64
     1.5     1.5     2.5     2.5
      98   104.1  104.11  106.64
Pier Skew, UpSta & Num, DnSta & Num=  ,1923.31, 4 ,1917.79, 4 , 3 , 3 , 0 ,,
     1.5     1.5     2.5     2.5
      98  104.18  104.19  106.64
     1.5     1.5     2.5     2.5
      98  104.18  104.19  106.64
Abutment Skew #Up #Dn= , 2 , 2
 1850.53 1881.16
  106.65   99.24
 1844.81 1875.39
  106.52   98.76
Abutment Skew #Up #Dn= , 2 , 2
 1929.94 1960.53
    99.4   106.6
 1923.52 1954.49
   98.72  106.51
BR Coef=-1 , 1 , 1 ,0.9, 0 ,,,0.8,-1,1.2,0,
WSPro=,,,, 1 ,,,, 0 ,,,, 0 ,,,,-1 ,-1 ,-1 , 0 , 0 , 0 , 0 , 0
BC Design=,, 0 ,, 0 ,,,,,,
BC Use User HTab Curves=0
BC User HTab FreeFlow(D)= 0

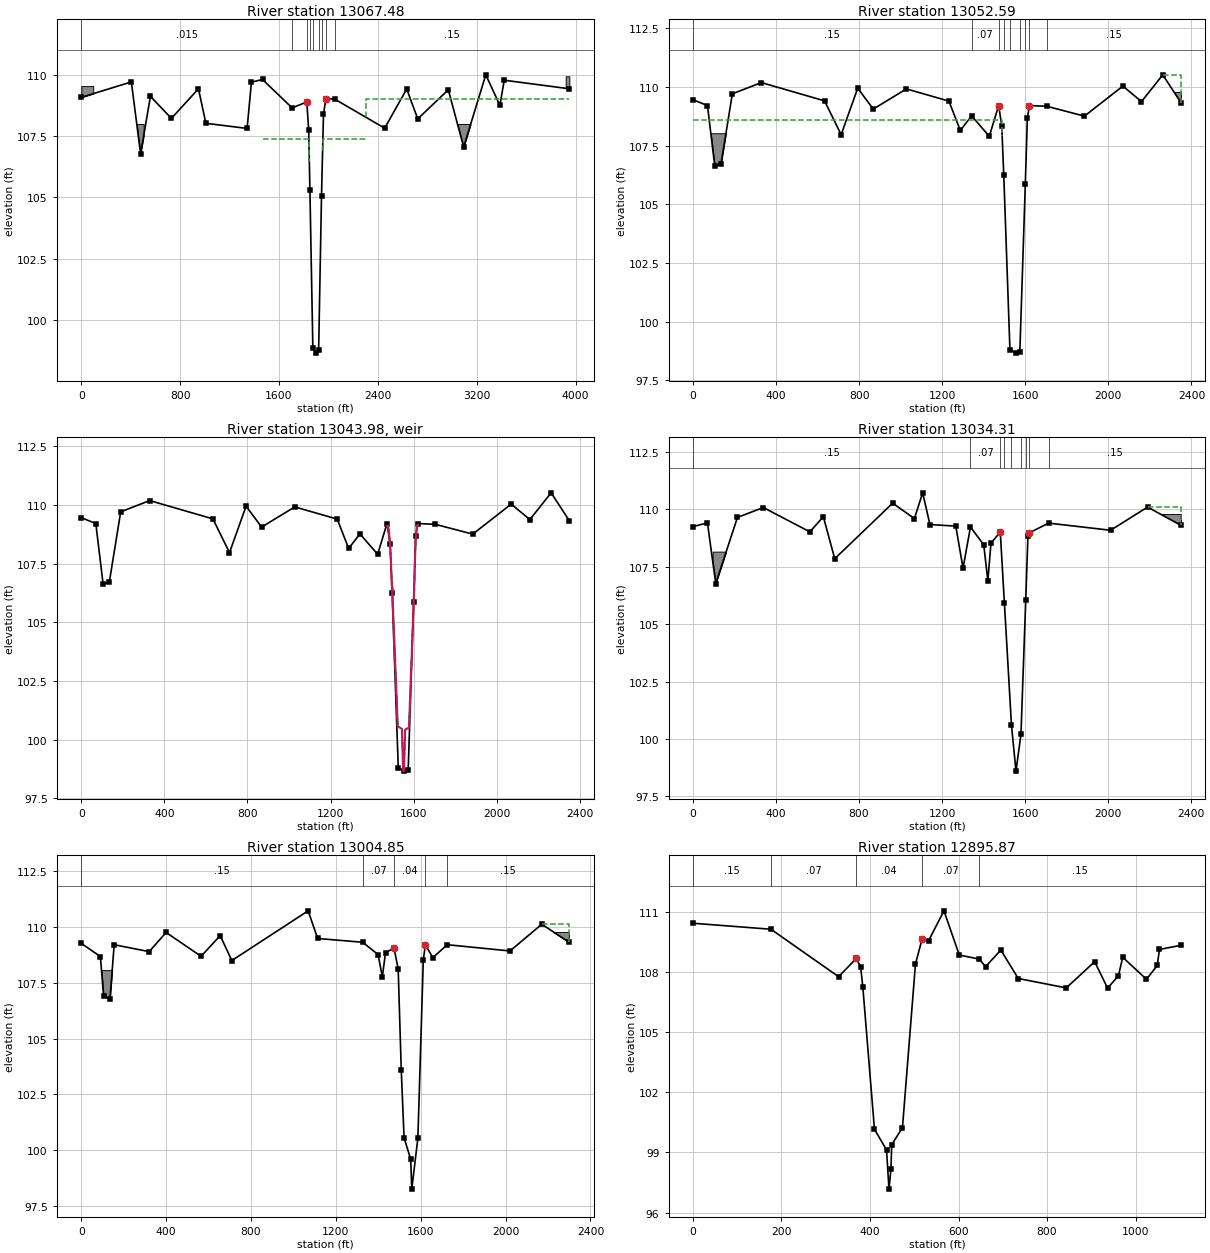
Type RM Length L Ch R = 1 ,13067.48,14.99,14.89,14.51
BEGIN DESCRIPTION:
Downstream Section - TANNER ROAD
END DESCRIPTION:
XS GIS Cut Line= 6
  3049041.24822613872539.3180832  3048901.39909713872545.8164298
 3048641.4045383 13872547.514261 3046542.007818513872497.5038624
 3046043.893329113872454.1220593 3045094.273837313872427.2326774
#Sta/Elev= 30
       0  109.09  404.98  109.72  479.73  106.78  559.47  109.13   728.9  108.23
  948.17  109.44 1007.97  108.03 1341.86  107.82 1376.74  109.71 1466.45  109.82
 1705.65  108.66 1825.25   108.9  1840.2  107.75 1850.17  105.29 1873.88   98.86
 1901.03   98.64 1920.75   98.75 1943.92  105.04    1960  108.41    1980  109.04
    2050  109.02    2455  107.83 2633.67  109.43 2722.78  108.21  2970.3   109.4
 3094.51  107.06 3273.57  110.01 3387.97  108.76 3422.79  109.79    3950  109.44
#Mann= 9 ,-1 , 0
       0    .015       0 1705.65     .07       0 1825.25     .04       0
 1850.17    .015       0 1873.88     .04       0 1920.75    .015       0
 1943.92     .04       0    1980     .07       0    2050     .15       0
#XS Ineff= 4 ,-1
       0 1466.45   108.8 1466.45 1845.45   107.4 1952.72    2305   107.4
    2305    3950  109.03
Permanent Ineff=
       F       F       F       F
#Block Obstruct= 4 ,-1
       0   96.55  109.55  444.85  504.65     108 3049.74 3149.22     108
 3920.18    3950  109.95
Bank Sta=1825.25,1980
XS Rating Curve= 0 ,0
Exp/Cntr=0.5,0.3

Type RM Length L Ch R = 1 ,13052.59,18.3,18.28,18.29
BEGIN DESCRIPTION:
Upstream Section - WEIR D/S OF TANNER ROAD
END DESCRIPTION:
XS GIS Cut Line= 5
  3048692.58783413872502.3955849 3047215.999908813872500.9999184
 3047067.999876713872497.9999243 3046544.012407613872465.8936893
 3046346.492461413872434.4944739
#Sta/Elev= 30
       0  109.46   69.84  109.21  104.76  106.64  134.69  106.71  189.56  109.71
  329.24  110.19  633.54  109.41  713.35  107.97  793.17  109.95  867.99  109.06
 1027.63  109.92 1232.15   109.4 1287.03  108.15 1341.39  108.77 1426.71   107.9
  1471.6  109.21 1486.46  108.36 1496.33  106.23 1525.91   98.81 1553.71   98.66
 1573.55   98.69 1599.95  105.86 1609.82  108.67 1619.69  109.21 1703.22  109.18
 1884.61  108.76  2069.6  110.04 2159.35  109.38 2261.79  110.52 2349.59  109.33
#Mann= 9 ,-1 , 0
       0     .15       0 1341.39     .07       0  1471.6     .04       0
 1496.33    .015       0 1525.91     .04       0 1573.55    .015       0
 1599.95     .04       0 1619.69     .07       0 1703.22     .15       0
#XS Ineff= 3 ,-1
       0 1488.49   108.6 1633.64 2261.79   108.6 2261.79 2349.59  110.52
Permanent Ineff=
       F       F       F
#Block Obstruct= 2 ,-1
   79.82  164.62  108.03 2261.79 2349.59   109.8
Bank Sta=1471.6,1619.69
XS Rating Curve= 0 ,0
Exp/Cntr=0.5,0.3

Type RM Length L Ch R = 5 ,13043.98,,,
BEGIN DESCRIPTION:
WEIR D/S OF TANNER ROAD
W671_300
END DESCRIPTION:
Node Name=WEIR DS TANNER
IW Pilot Flow=0
#Inline Weir SE= 18
  1471.6  109.11 1476.59  109.12 1481.52  108.85 1486.46  108.33 1491.39  107.46
 1496.33  106.32 1496.37  106.54 1523.61  100.57 1543.52  100.46 1549.03   98.69
 1553.71   98.66 1558.85  100.42 1577.37  100.52 1604.69  106.96 1604.88   107.4
 1609.82  108.49 1614.75  109.12 1619.69  109.15
IW Dist,WD,Coef,Skew,MaxSub,Min_El,Is_Ogee,SpillHt,DesHd
1.5,14,2.6,0,0.98,, 0 ,,,0.34,0.34,

Type RM Length L Ch R = 1 ,13034.31,29.48,29.46,29.48
BEGIN DESCRIPTION:
Downstream Section - WEIR D/S OF TANNER ROAD
END DESCRIPTION:
Node Name=I
XS GIS Cut Line= 5
  3048695.34143813872481.7430671 3047214.970711413872482.6935245
 3047066.970679313872479.6935305 3046545.256171513872448.4786979
 3046347.736225413872417.0794825
#Sta/Elev= 30
       0  109.25   69.78  109.41  109.66  106.77  214.33  109.65  338.94  110.08
  563.24  109.02  628.04  109.68  682.86  107.85  961.99  110.27 1066.66   109.6
 1106.54  110.72 1141.43  109.34 1266.04  109.27 1300.93  107.44 1336.71  109.23
 1400.62  108.46 1420.56  106.89 1435.51  108.53 1480.37  109.01 1500.11  105.94
 1534.37  100.59 1556.06    98.6 1579.98   100.2 1602.96  106.04  1613.6  108.83
 1618.54  108.97 1713.07   109.4 2011.68  109.09 2190.08   110.1 2351.05   109.3
#Mann= 9 ,-1 , 0
       0     .15       0 1336.71     .07       0 1480.37     .04       0
 1500.11    .015       0 1534.37     .04       0 1579.98    .015       0
 1602.96     .04       0 1618.54     .07       0 1713.07     .15       0
#XS Ineff= 3 ,-1
       0 1481.73   108.4 1645.32 2190.08   108.4 2190.08 2351.05   110.1
Permanent Ineff=
       F       F       F
#Block Obstruct= 2 ,-1
    94.7   159.5  108.16 2190.08 2351.05  109.79
Bank Sta=1480.37,1618.54
XS Rating Curve= 0 ,0
Exp/Cntr=0.5,0.3

Type RM Length L Ch R = 1 ,13004.85,106.86,108.98,111.52
XS GIS Cut Line= 6
  3048693.18691513872477.7250305 3048631.487235313872457.2755964
 3047217.590456813872453.2897119 3047069.590424713872450.2897179
 3046546.500263513872424.8442308 3046397.458566913872407.9164431
#Sta/Elev= 30
       0  109.27   89.93  108.68  104.92  106.91   134.9  106.77  154.89  109.21
  319.76   108.9   399.7  109.76  564.58  108.69  654.51  109.62  709.47   108.5
 1069.21  110.73 1114.17  109.49 1326.26  109.32 1398.97  108.77 1418.95  107.77
 1433.94  108.85 1473.91  109.06 1493.71  108.13  1508.1  103.61 1521.48  100.56
 1552.86   99.58  1557.7   98.25 1586.57  100.54 1612.13  108.54    1622  109.21
 1656.86  108.63 1725.32  109.21 2020.97  108.93 2170.65  110.13 2300.64  109.31
#Mann= 5 ,-1 , 0
       0     .15       0 1326.26     .07       0 1473.91     .04       0
    1622     .07       0 1725.32     .15       0
#XS Ineff= 3 ,-1
       0 1467.46     108 1660.75 2170.65     108 2170.65 2300.64  110.13
Permanent Ineff=
       F       F       F
#Block Obstruct= 2 ,-1
   94.93  149.89  108.07 2170.65 2300.64   109.8
Bank Sta=1473.91,1622
XS Rating Curve= 0 ,0
Exp/Cntr=0.3,0.1

Type RM Length L Ch R = 1 ,12895.87,111.18,111.35,111.29
XS GIS Cut Line= 5
  3047583.18027613872373.2737959 3047210.180038513872347.2738478
 3046953.180224513872330.2738819 3046682.088246913872321.5983743
 3046483.095534713872301.5498579
#Sta/Elev= 30
       0  110.45  176.14  110.15  329.04  107.78  368.92  108.69  378.86  108.27
  383.81  107.26  410.04  100.16  437.35   99.13  442.88   97.17  447.38   98.19
  449.01   99.39  473.34  100.24  502.69  108.41  517.55  109.66  532.41  109.58
  567.08  111.07  601.75  108.86  646.97  108.66  661.06  108.28  695.58  109.11
  735.03  107.69  843.52  107.22  907.58  108.53  936.84  107.21  961.23  107.82
  970.99  108.75 1024.65  107.65 1049.04  108.34 1053.92  109.14  1102.7  109.35
#Mann= 5 ,-1 , 0
       0     .15       0  176.14     .07       0  368.92     .04       0
  517.55     .07       0  646.97     .15       0
#XS Ineff= 2 ,-1
       0  368.92  108.69  517.55  1102.7  108.43
Permanent Ineff=
       F       F
Bank Sta=368.92,517.55
XS Rating Curve= 0 ,0
Exp/Cntr=0.3,0.1