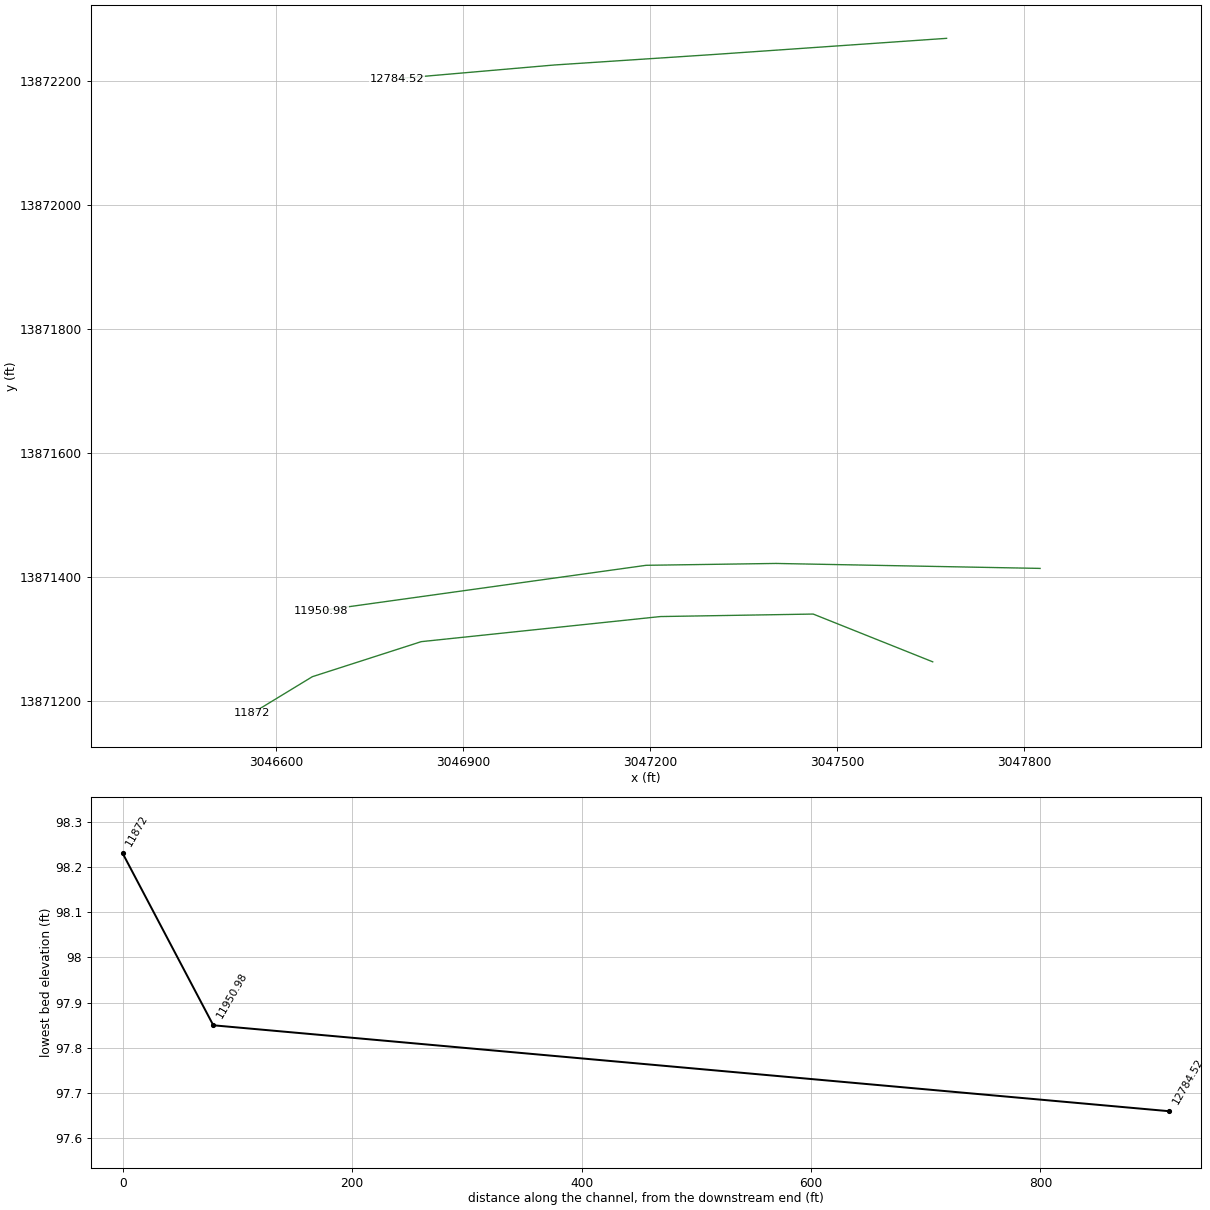
HEC-RAS study W167-01-00.prj: W167-01-00 2019 (Re-Study)

--- W167-01-00.g01 (geometry) --- (continued)

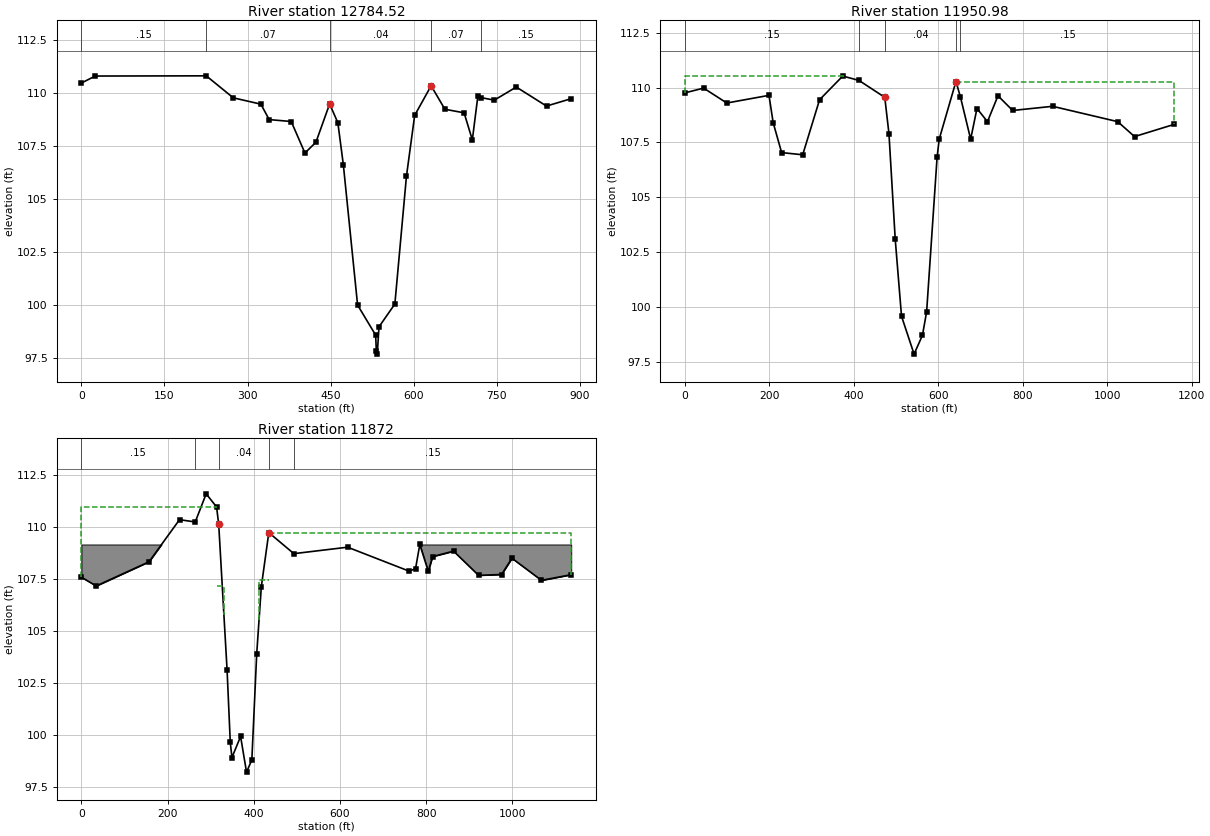
Type RM Length L Ch R = 1 ,12784.52,833.36,833.54,830.62
XS GIS Cut Line= 4
3047675.9999730313872268.00005633047303.0000628513872242.0001083
 3047045.999920713872225.0001423 3046794.000096613872202.9998582
#Sta/Elev= 30
       0  110.48   24.93  110.81  225.42  110.82   274.2  109.78  324.05  109.48
  339.01  108.75  378.86  108.66  403.62  107.17  423.44  107.68   448.2  109.49
  463.06   108.6  472.97  106.61  498.68   99.98  531.27   98.56  532.52   97.82
  534.18   97.66  537.32   98.95  565.97  100.03  586.89  106.07  601.75  108.95
  631.47  110.35  656.27  109.24  690.99  109.07  705.87  107.79  715.79  109.85
  721.36  109.79  745.55  109.67  785.23  110.29  839.79  109.39  884.43  109.74
#Mann= 5 ,-1 , 0
       0     .15       0  225.42     .07       0   448.2     .04       0
  631.47     .07       0  721.36     .15       0
#XS Ineff= 2 ,-1
       0   448.2  109.49  631.47  884.43  109.49
Permanent Ineff=
       F       F
Bank Sta=448.2,631.47
XS Rating Curve= 0 ,0
Exp/Cntr=0.3,0.1

Type RM Length L Ch R = 1 ,11950.98,76.15,78.98,85.38
Node Name=H
XS GIS Cut Line= 4
3047826.0000011213871414.00012393047401.9998648613871422.0001079
3047193.9999527813871419.00011393046672.0000125313871345.9999318
#Sta/Elev= 30
       0  109.76    44.9  109.98   99.78   109.3  199.57  109.65  209.54   108.4
   229.5  107.04  279.39  106.94   319.3  109.45  374.18  110.53  412.54  110.33
  473.61  109.56  483.51   107.9  498.37  103.08  513.23   99.58  542.95   97.85
  562.76   98.71  572.66   99.78  597.43  106.83  602.38  107.65  642.04  110.28
  652.76  109.57  676.85  107.65  691.77  109.05  716.63  108.45  741.49  109.63
   776.3  108.96  870.78  109.15 1024.92  108.45  1064.7  107.77 1159.18  108.33
#Mann= 5 ,-1 , 0
       0     .15       0  412.54     .07       0  473.61     .04       0
  642.04     .07       0  652.76     .15       0
#XS Ineff= 2 ,-1
       0  379.17  110.54  642.04 1159.18  110.28
Permanent Ineff=
       F       F
#Block Obstruct= 2 , 0
       0                 1024.92       0  108.33
Bank Sta=473.61,642.04
XS Rating Curve= 0 ,0
Exp/Cntr=0.5,0.3

Type RM Length L Ch R = 1 ,11872   ,73.6,74.29,73.91
BEGIN DESCRIPTION:
Upstream Section - LAKE CENTER RUN
END DESCRIPTION:
XS GIS Cut Line= 6
3047653.7106475213871263.52142223047461.9689050313871340.4572919
3047216.7003666913871336.42481973046833.2464091913871295.9997037
3046658.5722178713871239.5664176 3046561.8296292 13871180.446129
#Sta/Elev= 30
       0  107.58   34.31  107.16  156.85  108.32  227.61  110.34  264.06  110.23
  289.44  111.58  313.58  110.95  318.54  110.11  337.93  103.13  345.37   99.66
  349.19   98.93  369.32   99.94  383.04   98.23  395.41   98.82  406.63  103.89
  417.41  107.13  434.74  109.72  492.85  108.71  617.59  109.02  760.39  107.87
  775.16  107.99  785.01  109.15  804.71  107.86  814.56  108.57  863.37  108.83
  921.42  107.67   974.6  107.71  998.77  108.49  1067.3  107.43 1136.32   107.7
#Mann= 5 ,-1 , 0
       0     .15       0  264.06     .07       0  318.54     .04       0
  434.74     .07       0  492.85     .15       0
#XS Ineff= 4 ,-1
       0  313.58  110.95  313.58  330.67  107.16  412.12  434.74  107.43
  434.74 1136.32  109.72
Permanent Ineff=
       F       F       F       F
#Block Obstruct= 2 ,-1
       0  193.98  109.15  785.01 1136.32  109.15
Bank Sta=318.54,434.74
XS Rating Curve= 0 ,0
Exp/Cntr=0.5,0.3