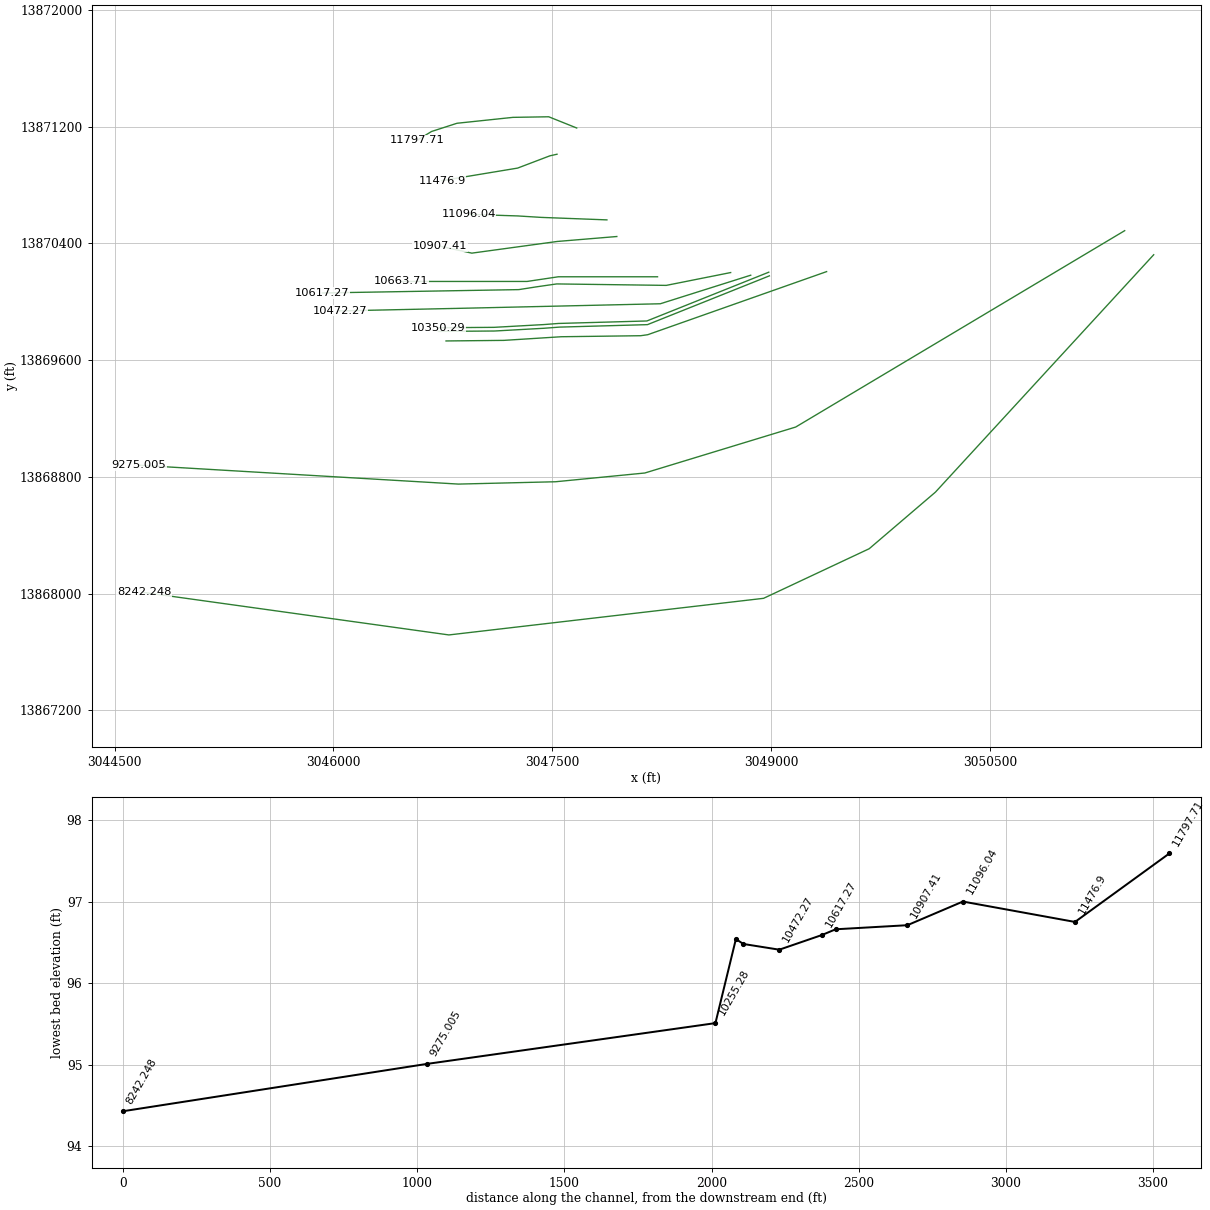
HEC-RAS study W167-01-00.prj: W167-01-00 2019 (Re-Study)

--- W167-01-00.g01 (geometry) --- (continued)

Type RM Length L Ch R = 3 ,11834.84,,,
BEGIN DESCRIPTION:
LAKE CENTER RUN
END DESCRIPTION:
Node Name=LAKE CENTER RUN
Bridge Culvert--1,0,-1,-1, 0
Deck Dist Width WeirC Skew NumUp NumDn MinLoCord MaxHiCord MaxSubmerge Is_Ogee
15,54,2.6,0, 60, 60, , , 0.98, 0, 0,0,,
       0     4.9     9.8   29.41   39.21   44.11   49.02   53.92   58.82   93.13
   98.03  102.93  142.14  180.31  189.42  203.08  212.63  227.61  246.81  251.55
  256.29  261.02  275.23  289.44   291.4     319  319.69   319.8     369     407
   416.7  416.81   416.9  420.64  448.84   478.5  503.45  553.37  578.19  597.89
  632.36  671.75  676.68  696.37  725.92  755.46  780.09  789.94  804.71   824.4
  839.18  848.85  873.04  897.23  935.93 1027.87  1032.8 1047.59 1062.37 1136.32
  106.29  106.27  106.11  106.36  106.31  106.38  106.61  106.57  106.71  107.02
   107.1  107.36  107.85  108.52  108.52  108.85   108.9   109.2  109.41  109.55
  109.51   109.7  109.92  109.94  110.72  111.08  111.09  115.69  115.93  115.69
  115.63  111.03  111.03   110.6  110.13  109.91  109.49  108.92  108.53  108.42
  107.82  107.66  107.52  107.58  107.42  107.38  107.17  107.24  106.92  107.22
  107.17  107.25  107.04  106.95  106.92  106.51   106.6  106.46  106.52  106.25
                                                                                
                                                                                
                                          105.61  105.61  105.61  105.84  105.54
  105.54  105.54  105.54
                                                                                
                                                                                
       0     4.9     9.8   29.41   39.21   44.11   49.02   53.92   58.82   93.13
   98.03  102.93  142.14  180.31  189.42  203.08  212.63  227.61  246.81  251.55
  256.29  261.02  275.23  289.44  294.18  303.65  328.46     333  333.69   333.8
     383     421   430.7  430.81   430.9  434.74  453.54   478.5  503.45  553.37
  578.19  597.89  632.36  671.75  676.68  696.37  755.46  780.09  789.94  804.71
   824.4  839.18  848.85  897.23  935.93 1027.87  1032.8 1047.59 1062.37  1116.6
  106.29  106.27  106.11  106.36  106.31  106.38  106.61  106.57  106.71  107.02
   107.1  107.36  107.85  108.52  108.52  108.85   108.9   109.2  109.41  109.55
  109.51   109.7  109.92  109.94  110.09  110.02  110.45  111.08  111.09  115.69
  115.93  115.69  115.63  111.03  111.03  110.32  110.08  109.91  109.49  108.92
  108.53  108.42  107.82  107.66  107.52  107.58  107.38  107.17  107.24  106.92
  107.22  107.17  107.25  106.95  106.92  106.51   106.6  106.46  106.52  106.29
                                                                                
                                                                                
                                                          105.66  105.66  105.66
   105.8   105.5   105.5   105.5   105.5
                                                                                
                                                                                
Pier Skew, UpSta & Num, DnSta & Num=  ,369, 2 ,383, 2 , 0 , 0 , 0 ,,
     3.8     3.8
      97     107
     3.8     3.8
      97     107
BR Coef=-1 , 1 , 1 ,0.9, 0 ,,,0.8,-1,1.2,0,
WSPro=,,,, 1 ,,,, 0 ,,,, 0 ,,,,-1 ,-1 ,-1 , 0 , 0 , 0 , 0 , 0
BC Design=,, 0 ,, 0 ,,,,,,
BC Use User HTab Curves=0
BC User HTab FreeFlow(D)= 0

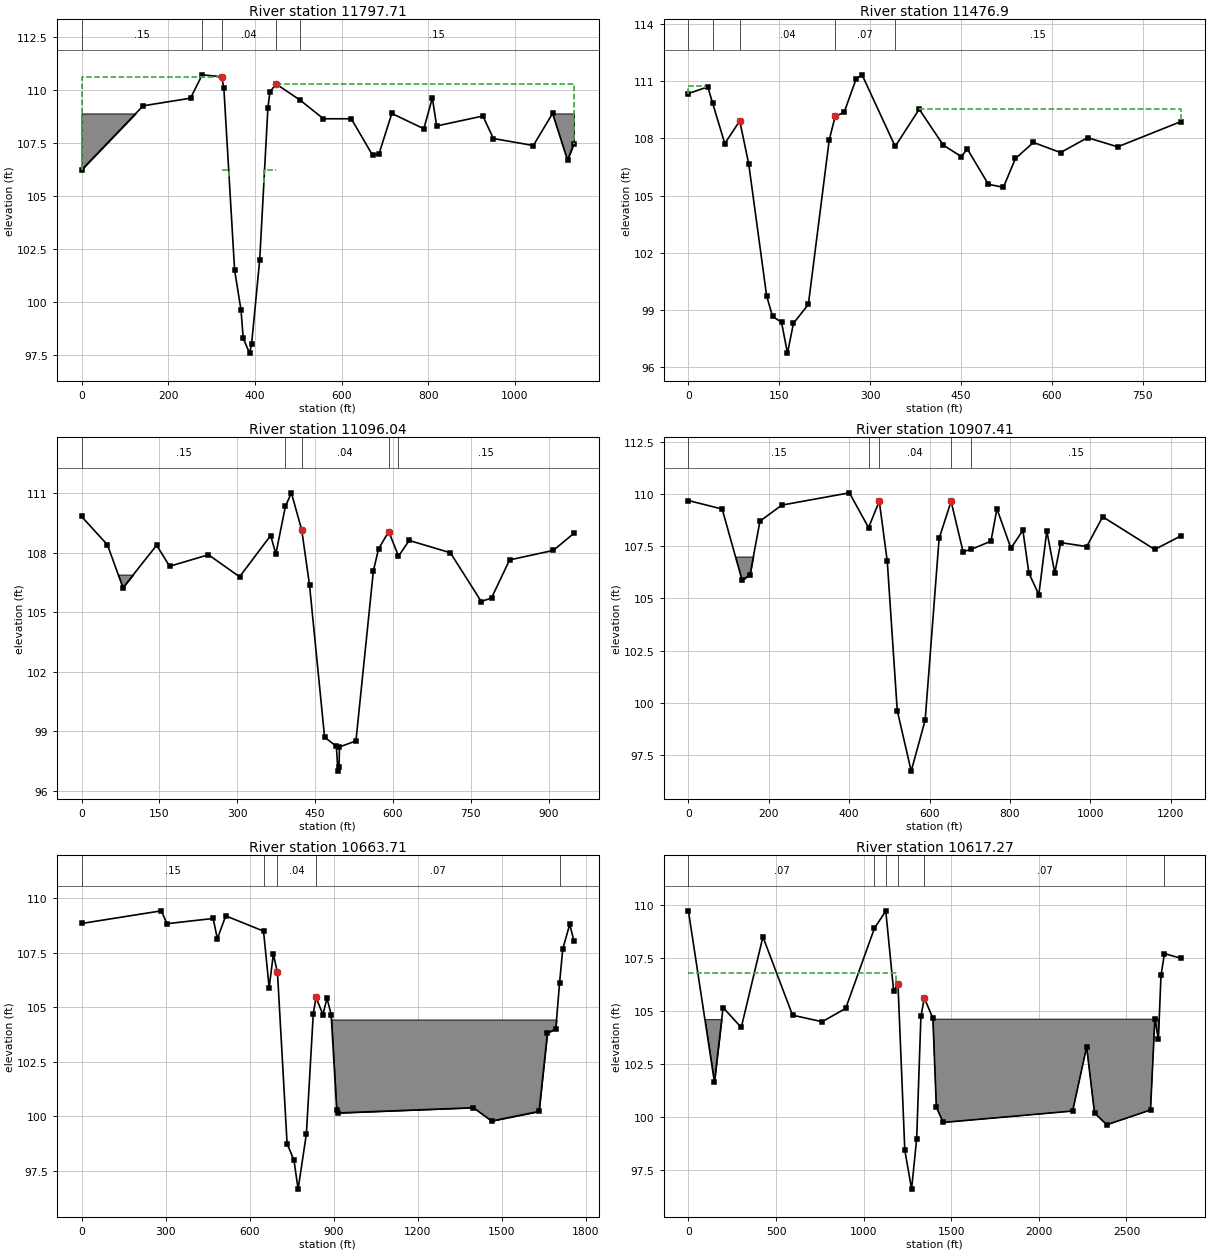
Type RM Length L Ch R = 1 ,11797.71,308.26,320.81,335.39
BEGIN DESCRIPTION:
Downstream Section - LAKE CENTER RUN
END DESCRIPTION:
Node Name=G
XS GIS Cut Line= 6
3047667.9688211113871190.78698763047476.2270786213871267.7228574
3047230.9585402813871263.69038513046847.5045827813871223.2652691
3046672.83039144 13871166.8319833046576.0878027813871107.7116944
#Sta/Elev= 30
       0  106.22  142.14  109.24  251.55   109.6  278.46   110.7   323.5  110.61
  328.46  110.07  353.27   101.5  368.15    99.6  373.12   98.29  387.74   97.59
  392.44   98.01  411.24     102  430.04  109.12  434.74  109.89  448.84  110.27
  503.61  109.52  558.36  108.63  622.51  108.63  671.75  106.91  686.53  106.98
  716.07  108.88  789.94  108.16  809.63  109.61  819.48  108.29  926.26  108.76
  950.43   107.7 1042.66  107.37 1087.02  108.88 1121.53  106.68 1136.32  107.46
#Mann= 5 ,-1 , 0
       0     .15       0  278.46     .07       0   323.5     .04       0
  448.84     .07       0  503.61     .15       0
#XS Ineff= 4 ,-1
       0   323.5  110.61   323.5     341   106.2   420.8  448.84   106.2
  448.84 1136.32  110.27
Permanent Ineff=
       F       F       F       F
#Block Obstruct= 2 ,-1
       0  137.24  108.88 1087.02 1136.32  108.88
Bank Sta=323.5,448.84
XS Rating Curve= 0 ,0
Exp/Cntr=0.5,0.3

Type RM Length L Ch R = 1 ,11476.9 ,404.34,380.86,357.45
XS GIS Cut Line= 4
3047532.9999309513871010.99994563047484.0000289413870999.9999676
3047263.0001428613870916.00013563046743.9998685313870829.9999795
#Sta/Elev= 30
       0  110.34   31.96  110.69   40.04  109.83   60.07  107.72    84.7  108.91
   99.47  106.67  129.03   99.76  138.88   98.67  153.66   98.37  163.51   96.75
  173.36   98.31  197.99    99.3  232.46  107.92  242.31  109.15  257.09  109.36
  276.79   111.1  286.64  111.32  341.28  107.57  380.94  109.52  420.65  107.64
  450.42  107.04  460.35  107.44  495.09  105.59  519.91  105.43  539.76  106.94
  569.54  107.78   614.2  107.25  658.87  108.03   708.5  107.55  812.72  108.87
#Mann= 5 ,-1 , 0
       0     .15       0   40.04     .07       0    84.7     .04       0
  242.31     .07       0  341.28     .15       0
#XS Ineff= 2 ,-1
       0   27.39  110.74  380.94  812.72  109.52
Permanent Ineff=
       F       F
Bank Sta=84.7,242.31
XS Rating Curve= 0 ,0
Exp/Cntr=0.3,0.1

Type RM Length L Ch R = 1 ,11096.04,179.13,188.63,199.56
XS GIS Cut Line= 4
3047874.9999031113870560.99986143047426.0001449413870578.0001554
3047264.0001408613870588.0001354 3046927.000158713870599.0001134
#Sta/Elev= 30
       0  109.83   49.92   108.4   79.88  106.24  144.78  108.38  169.74  107.32
  244.63   107.9  304.54  106.79  364.45  108.87  374.43  107.94  392.87  110.34
  404.39  111.02  424.36  109.14  439.34  106.37  468.34   98.71  491.07   98.25
     494      97  496.19   97.23  497.04   98.22  528.78   98.52  562.45   107.1
  572.28  108.19  591.96  109.07  610.77  107.83  631.46  108.62   710.8     108
   770.3  105.54  790.14  105.73  824.85  107.64  909.14  108.12  948.81  108.98
#Mann= 5 ,-1 , 0
       0     .15       0  392.87     .07       0  424.36     .04       0
  591.96     .07       0  610.77     .15       0
#XS Ineff= 2 ,-1
       0  144.78   107.8   710.8  948.81   107.8
Permanent Ineff=
       F       F
#Block Obstruct= 1 ,-1
   68.89  104.84   106.9
Bank Sta=424.36,591.96
XS Rating Curve= 0 ,0
Exp/Cntr=0.3,0.1

Type RM Length L Ch R = 1 ,10907.41,244.42,243.69,304.23
XS GIS Cut Line= 4
3047943.0000951913870447.00008933047533.9999289413870413.0001574
3046949.0001146913870332.99998933046729.9998965313870380.9998933
#Sta/Elev= 30
       0   109.7   84.06  109.29  133.51  105.87  153.29  106.14  178.01  108.71
   232.4  109.48  400.52  110.07  448.21   108.4  474.91  109.67  494.76  106.78
  519.57   99.62   554.3   96.71  589.03   99.16  623.76  107.88  653.54  109.66
  683.31  107.25  702.92  107.35  752.77  107.75  767.65   109.3  802.39  107.41
  832.16  108.27  847.04  106.22  871.85  105.18   891.7  108.24  911.54  106.22
  926.43  107.68  990.93  107.49 1030.75  108.92 1160.28  107.35 1225.05     108
#Mann= 5 ,-1 , 0
       0     .15       0  448.21     .07       0  474.91     .04       0
  653.54     .07       0  702.92     .15       0
#XS Ineff= 2 ,-1
       0  370.85   107.5  767.65 1225.05   107.5
Permanent Ineff=
       F       F
#Block Obstruct= 1 ,-1
  118.67  163.18  107.01
Bank Sta=474.91,653.54
XS Rating Curve= 0 ,0
Exp/Cntr=0.3,0.1

Type RM Length L Ch R = 1 ,10663.71,47.02,46.44,61.15
XS GIS Cut Line= 4
3048221.9998652813870170.99998523047541.9999129513870170.9999852
3047328.0000128613870139.00004923046466.0000964413870139.0000492
#Sta/Elev= 30
       0  108.83     285  109.41     305  108.82     470  109.06     485  108.13
     515  109.18  649.92  108.48     670  105.89  684.92  107.42  699.67  106.59
   734.1   98.74  758.68   97.98  773.44   96.66  802.94   99.19  827.53  104.69
  837.37  105.44  861.96  104.66  876.71  105.41  891.46  104.65  911.33  100.27
  916.31  100.15 1399.62  100.39  1464.4   99.78 1633.81  100.22  1663.7  103.81
  1693.6     104 1707.23  106.12 1718.51  107.66 1743.42  108.79 1758.37  108.03
#Mann= 5 ,-1 , 0
       0     .15       0  649.92     .07       0  699.67     .04       0
  837.37     .07       0 1707.23     .15       0
#XS Ineff= 2 ,-1
       0  684.92  107.42  876.71 1758.37  105.41
Permanent Ineff=
       F       F
#Block Obstruct= 1 ,-1
   847.2 1703.56  104.43
Bank Sta=699.67,837.37
XS Rating Curve= 0 ,0
Exp/Cntr=0.3,0.1

Type RM Length L Ch R = 1 ,10617.27,268.1,145,135.91
XS GIS Cut Line= 6
  3048723.329243 13870199.912657 3048282.000073413870112.0001032
 3047530.999934913870122.0000832 3047391.999884913870102.0001232
 3047271.000126913870083.0001612 3045924.999866113870059.9998791
#Sta/Elev= 30
       0  109.74  148.35  101.65   197.8  105.17  301.65  104.23  425.27  108.51
  594.24  104.81  763.36   104.5  897.66  105.13  1061.8  108.92 1126.46  109.73
 1171.22  105.96 1196.09  106.27 1234.96   98.44  1273.7   96.59 1302.76   98.97
 1326.97  104.75  1346.4  105.62 1395.39  104.66 1414.99  100.47 1454.18   99.74
 2192.94  100.28 2272.83  103.31 2317.76  100.19 2387.66   99.63  2637.3  100.33
 2662.27  104.65 2682.24  103.67 2697.22  106.69 2716.87  107.72 2810.18   107.5
#Mann= 6 ,-1 , 0
       0     .07       0  1061.8     .15       0 1126.46     .07       0
 1196.09     .04       0  1346.4     .07       0 2716.87     .15       0
#XS Ineff= 2 ,-1
       0 1186.15  106.82  1346.4 2810.18  105.62
Permanent Ineff=
       F       F
#Block Obstruct= 2 ,-1
       0  212.64  104.62  1346.4 2697.22  104.62
Bank Sta=1196.09,1346.4
XS Rating Curve= 0 ,0
Exp/Cntr=0.3,0.1

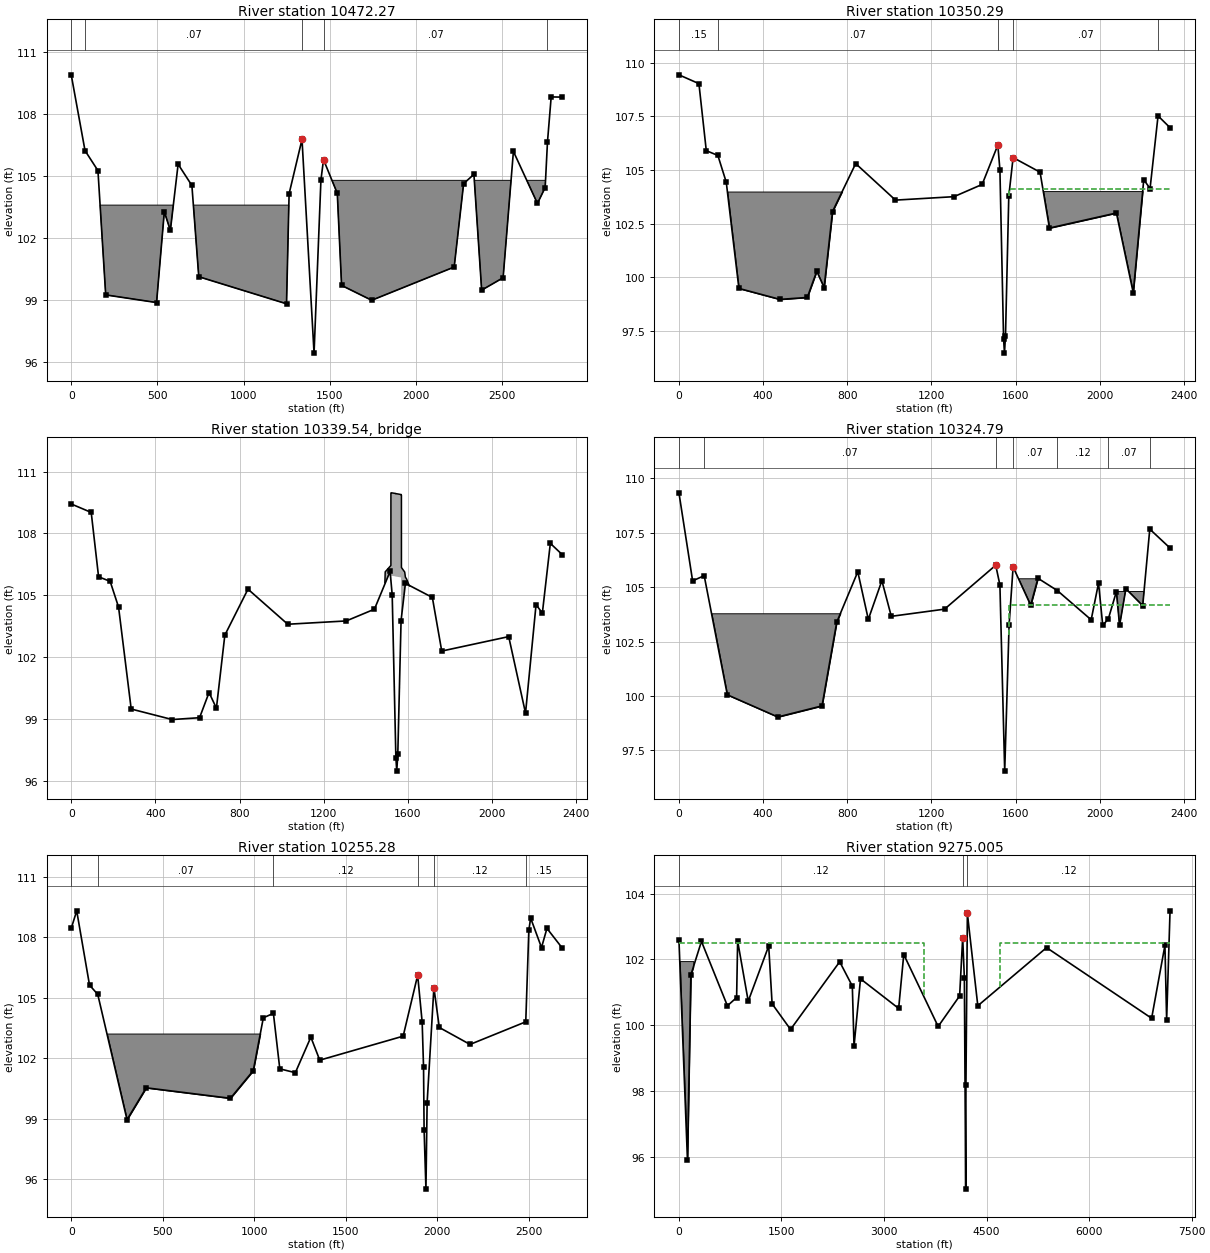
Type RM Length L Ch R = 1 ,10472.27,136.71,121.99,165.15
Node Name=F
XS GIS Cut Line= 4
  3048860.81125113870181.7909741 3048241.000155413869986.0000271
 3046923.999836613869956.0000871 3046042.999958213869937.0001251
#Sta/Elev= 30
       0  109.89      80  106.22     155  105.25     200   99.23     495   98.86
     540  103.26     575  102.35     620  105.56   699.9  104.53  739.82  100.11
 1248.79    98.8 1263.76  104.13 1338.61  106.76 1408.47   96.41 1448.39   104.8
 1463.36  105.78  1543.2  104.15 1568.15   99.69 1742.79   98.97 2221.25  100.58
 2276.01  104.62 2335.75  105.07 2380.56   99.46 2505.02  100.06 2564.77  106.18
 2704.17  103.66 2748.97  104.43 2762.44  106.65 2783.82  108.82 2848.55  108.81
#Mann= 5 ,-1 , 0
       0     .15       0      80     .07       0 1338.61     .04       0
 1463.36     .07       0 2762.44     .15       0
#XS Ineff= 2 ,-1
       0 1338.61  104.33 1463.36 2848.55  105.78
Permanent Ineff=
       F       F
#Block Obstruct= 2 ,-1
       0 1272.74  103.58 1463.36 2758.93  104.78
Bank Sta=1338.61,1463.36
XS Rating Curve= 0 ,0
Exp/Cntr=0.5,0.3

Type RM Length L Ch R = 1 ,10350.29,25.34,25.49,28.49
BEGIN DESCRIPTION:
Upstream Section - ACCESS RD
END DESCRIPTION:
Node Name=E
XS GIS Cut Line= 6
  3048984.52097813870202.4182294 3048148.9429248 13869868.039305
 3047543.643610513869851.0682103 3047442.274718713869843.3448006
 3047100.846267713869824.3802716  3046716.02945213869821.7080328
#Sta/Elev= 30
       0  109.43      95  109.02     130   105.9     185  105.68     225  104.43
     285   99.49     480   98.98     610   99.07     655  100.29     690   99.53
     730  103.07     840   105.3 1029.05   103.6    1307  103.76 1441.01  104.33
 1515.48  106.16 1525.42  105.02 1542.89   97.14 1547.08   96.48 1551.97   97.29
  1567.6  103.78 1588.16  105.58 1716.23   104.9 1760.84   102.3  2079.1     103
 2159.06   99.29 2209.04  104.55 2239.03  104.14 2276.94  107.52 2333.98  106.97
#Mann= 5 ,-1 , 0
       0     .15       0     185     .07       0 1515.48     .04       0
 1588.16     .07       0 2276.94     .15       0
#XS Ineff= 3 ,-1
       0     845   104.9     845 1520.65  104.33 1567.59 2333.98  104.12
Permanent Ineff=
       F       F       F
#Block Obstruct= 2 ,-1
     185     845     104 1696.41 2249.02  104.02
Bank Sta=1515.48,1588.16
XS Rating Curve= 0 ,0
Exp/Cntr=0.5,0.3

Type RM Length L Ch R = 3 ,10339.54,,,
BEGIN DESCRIPTION:
ACCESS RD
END DESCRIPTION:
Node Name=ACCESS RD
Bridge Culvert--1,0,-1,-1, 0
Deck Dist Width WeirC Skew NumUp NumDn MinLoCord MaxHiCord MaxSubmerge Is_Ogee
8,6.8,2.6,0, 31, 31, , , 0.98, 0, 0,0,,
 1490.65  1492.2 1519.19  1519.3 1519.41  1520.2 1520.31  1520.4  1522.4  1540.7
  1540.8  1541.1  1542.8    1545  1547.1  1548.3  1549.8  1549.9  1565.3 1567.59
  1567.7  1567.8 1569.19  1569.3 1569.41  1584.9 1588.16 1592.92 1597.68 1602.44
  1607.2
  105.62  106.14  106.45  109.95  109.95  109.97  109.97  109.97  109.97  109.94
  109.94  109.93  109.93  109.93  109.92  109.92  109.92  109.92  109.89  109.89
  109.89  109.89  109.85  109.85  106.35  106.13  105.88  105.81   105.7  105.57
  105.46
          104.54  104.54  104.54  104.54  104.54  104.54  105.95  105.95  105.92
  105.92  105.91  105.91  105.91   105.9   105.9   105.9   105.9  105.87  105.87
  99.471  93.654  12.797   6.399
        
 1490.65  1492.2 1519.19  1519.3 1519.41  1520.2 1520.31  1520.4  1522.4  1540.7
  1540.8  1541.1  1542.8    1545  1547.1  1548.3  1549.8  1549.9  1565.3 1567.59
  1567.7  1567.8 1569.19  1569.3 1569.41  1584.9 1588.16 1592.92 1597.68 1602.44
  1607.2
  105.62  106.14  106.45  109.95  109.95  109.97  109.97  109.97  109.97  109.94
  109.94  109.93  109.93  109.93  109.92  109.92  109.92  109.92  109.89  109.89
  109.89  109.89  109.85  109.85  106.35  106.13  105.88  105.81   105.7  105.57
  105.46
          104.95  104.95  104.95  104.95  104.95  104.95  105.92  105.92  105.89
  105.89  105.88  105.88  105.88  105.87  105.87  105.87  105.87  105.84  105.84
  99.443  93.628  12.794   6.397
        
Abutment Skew #Up #Dn= , 2 , 2
  1520.2  1540.8
  105.95   97.11
  1520.2  1540.8
  105.92   97.08
Abutment Skew #Up #Dn= , 2 , 2
  1549.9 1567.79
   97.29  105.87
  1549.9 1567.79
   97.26  105.84
BR Coef=-1 , 0 , 0 ,, 0 ,,,0.8,-1,,0,
WSPro=,,,, 1 ,,,, 0 ,,,, 0 ,,,,-1 ,-1 ,-1 , 0 , 0 , 0 , 0 , 0
BC Design=,, 0 ,, 0 ,,,,,,
BC Use User HTab Curves=0
BC User HTab FreeFlow(D)= 0

Type RM Length L Ch R = 1 ,10324.79,70.26,69.51,71.14
BEGIN DESCRIPTION:
Downstream Section - ACCESS RD
END DESCRIPTION:
Node Name=D
XS GIS Cut Line= 6
  3048988.74537913870177.2781879 3048153.167325813869842.8992634
 3047547.868011413869825.9281688 3047446.4991197 13869818.204759
 3047105.0706687  13869799.24023  3046720.25385313869796.5679913
#Sta/Elev= 30
       0  109.34      65  105.29     120  105.53     230  100.05     470   99.03
     680   99.54     750  103.39     850  105.71     900  103.52  964.52   105.3
  1009.2  103.66 1262.33  103.99 1505.54  106.01 1525.42   105.1 1548.17   96.54
 1569.11  103.27 1588.16  105.93 1671.63  104.17 1706.32  105.41 1798.92  104.84
 1959.16   103.5 1994.14  105.19 2014.13  103.24 2040.92  103.55  2079.1   104.8
 2094.09  103.24 2124.08  104.93 2204.04  104.15 2237.64  107.67 2333.98   106.8
#Mann= 7 ,-1 , 0
       0     .15       0     120     .07       0 1505.54     .04       0
 1588.16     .07       0 1798.92     .12       0 2040.92     .07       0
 2237.64     .15       0
#XS Ineff= 3 ,-1
       0     850   104.7     850  1520.4   104.2 1567.59 2333.98   104.2
Permanent Ineff=
       T       F       F
#Block Obstruct= 3 ,-1
     120     850   103.8 1588.16 1706.32  105.41  2079.1 2219.04   104.8
Bank Sta=1505.54,1588.16
XS Rating Curve= 0 ,0
Exp/Cntr=0.5,0.3

Type RM Length L Ch R = 1 ,10255.28,962.4,980.28,985.89
Node Name=C
XS GIS Cut Line= 6
  3049380.98311113870206.3945994 3048154.9999993 13869774.000123
 3048107.0000953 13869767.000137 3047561.9998729 13869760.000151
 3047168.156500513869734.9982325 3046772.322974613869731.0920724
#Sta/Elev= 30
       0  108.43      30   109.3     100  105.62     145  105.16     305   98.95
     410  100.53     870  100.01     995  101.38    1050     104    1105  104.22
    1140  101.47    1225  101.28  1309.7  103.04 1358.42   101.9 1814.27  103.09
 1893.55  106.11 1918.19  103.78 1925.69  101.54 1928.69   98.45 1938.76   95.51
 1945.23   99.79 1982.24  105.49 2011.87  103.52 2179.76  102.68 2484.33   103.8
 2501.17  108.34 2511.07  108.94 2570.45  107.48 2600.14  108.43 2684.26  107.45
#Mann= 6 ,-1 , 0
       0     .15       0     145     .07       0    1105     .12       0
 1893.55     .04       0 1982.24     .12       0 2484.33     .15       0
#XS Ineff= 3 ,-1
       0    1105  104.22    1105 1863.91   103.5 2007.61 2684.26   103.5
Permanent Ineff=
       T       F       F
#Block Obstruct= 1 ,-1
     145    1065  103.22
Bank Sta=1893.55,1982.24
XS Rating Curve= 0 ,0
Exp/Cntr=0.3,0.1

Type RM Length L Ch R = 1 ,9275.005,1011.39,1032.76,1036.78
Node Name=B
XS GIS Cut Line= 6
3051424.0000229513870487.00000943049168.9999397713869141.0000767
3048135.0000392813868826.00005053047522.9999509513868765.9998424
3046856.9999706113868749.99987443044665.2976611113868879.4973188
#Sta/Elev= 30
       0   102.6  124.82   95.89  174.74  101.53  329.52  102.55  708.96  100.59
  843.77  100.84  858.75  102.56 1013.52  100.73 1313.08  102.41 1363.01  100.65
 1632.62   99.87 2351.57  101.93  2536.3  101.19 2561.26   99.36 2656.05  101.41
 3213.95  100.51 3288.67  102.15 3791.81   99.96 4105.78  100.89 4150.64  102.66
 4175.14  101.44  4194.9   95.01 4198.28   98.17 4219.26   103.4  4371.9  100.59
 5377.59  102.36 6914.44  100.21 7109.04  102.43 7133.99  100.16 7183.89  103.48
#Mann= 3 ,-1 , 0
       0     .12       0 4150.64     .04       0 4219.26     .12       0
#XS Ineff= 2 ,-1
       0 3588.97   102.5 4700.09 7183.89   102.5
Permanent Ineff=
       T       T
#Block Obstruct= 1 ,-1
       0  209.69  101.95
Bank Sta=4150.64,4219.26
XS Rating Curve= 0 ,0
Exp/Cntr=0.3,0.1

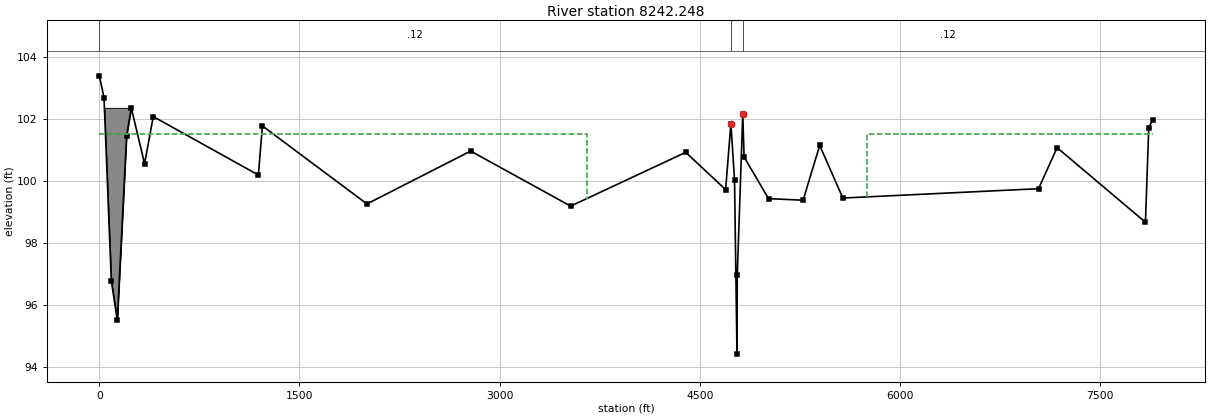
Type RM Length L Ch R = 1 ,8242.248,0,0,0
Node Name=A
XS GIS Cut Line= 6
3051622.9999530313870322.00001133050126.9999922813868694.9999844
3049672.9999160313868307.00010433048949.0000516913867967.0001281
3046792.0001006113867715.99997393044701.8943726913868007.1145492
#Sta/Elev= 30
       0  103.38   34.92  102.68   89.78   96.79  134.67   95.52   204.5  101.45
  239.42  102.35  339.18  100.55  404.02  102.07  1192.1  100.19 1222.03  101.77
  2005.8   99.26 2783.09  100.96 3532.85   99.19  4395.5  100.92 4694.24   99.72
 4733.79  101.84 4761.13  100.03 4779.38   94.43 4781.62   96.98 4822.76  102.15
 4832.65  100.77 5015.96   99.43 5274.95   99.38 5399.47  101.14 5572.86   99.45
 7039.49   99.75 7178.88  101.07 7840.96   98.67 7865.85  101.71 7895.72  101.97
#Mann= 3 ,-1 , 0
       0     .12       0 4733.79     .04       0 4822.76     .12       0
#XS Ineff= 2 ,-1
       0 3652.21   101.5 5750.69 7895.72   101.5
Permanent Ineff=
       T       T
#Block Obstruct= 1 ,-1
       0  239.42  102.35
Bank Sta=4733.79,4822.76
XS Rating Curve= 0 ,0
Exp/Cntr=0.3,0.1

Chan Stop Cuts=-1
Use User Specified Reach Order=0
Composite Channel Slope=5